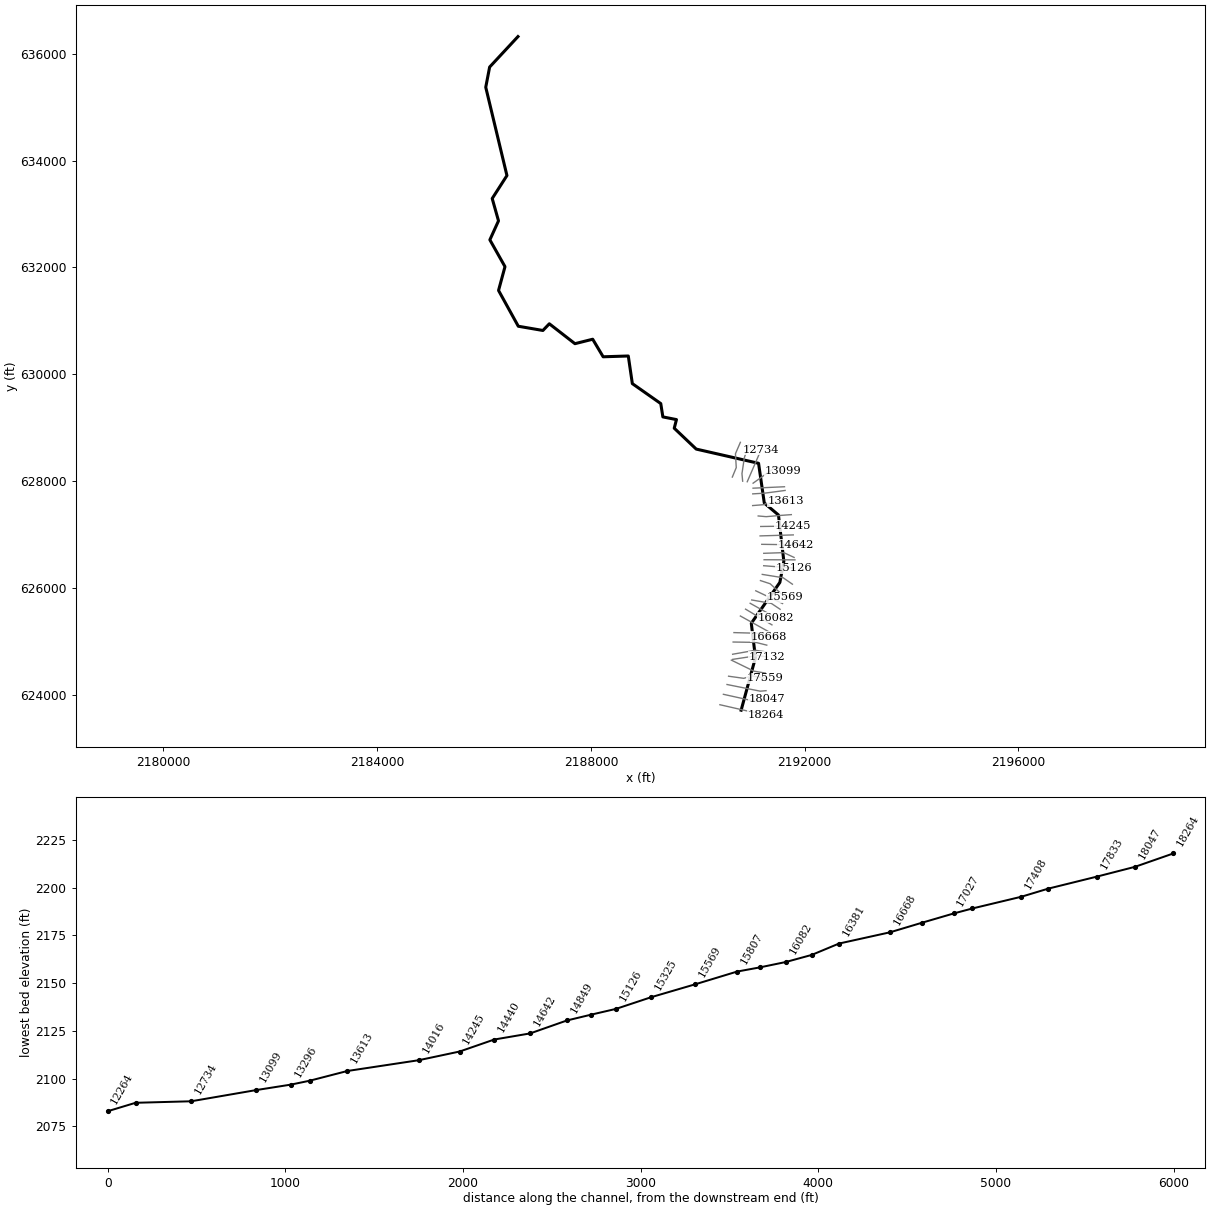
--- MFRFBUCKRV.prj (project) ---

Proj Title=MFRFBUCKRV
Current Plan=p01
Default Exp/Contr=0,0
English Units
Geom File=g01
Flow File=f01
Plan File=p01
Background Map Layer=Inundation Boundary (P100yr Value_0)
BEGIN DESCRIPTION:
----------MODEL BY WOOD PLC 2022----------
AFH study
Randolph County, WV
HEC-RAS Version: RAS 6.2
Vertical Datum: NAVD88
Projection: NAD 1983 StatePlane West Virginia S FIPS 4702 (US Feet)
Terrain: 1-meter LIDAR (FEMA Region III 3DEP collected 2016-2018)
Land Use: 2019 NLCD
Hydrologic Method:
WV SIR2010-5033 regression equations
Additional Model Notes:
This reach continues past the county boundary. Additional XS past boundary have been added as of 8 July 2022
END DESCRIPTION:
DSS Export Rating Curves= 0
DSS Export Rating Curve Sorted= 0
DSS Export Volume Flow Curves= 0
DXF OffsetX= 0
DXF OffsetY= 0
DXF ScaleX= 0
DXF ScaleY= 0

--- MFRFBUCKRV.p01 (plan) ---

Plan Title=Floodplain
Program Version=6.20
Short Identifier=Floodplain
Geom File=g01
Flow File=f01
Subcritical Flow
K Sum by GR= 0
Std Step Tol= 0.01
Critical Tol= 0.01
Num of Std Step Trials= 20
Max Error Tol= 0.3
Flow Tol Ratio= 0.001
Split Flow NTrial= 30
Split Flow Tol= 0.02
Split Flow Ratio= 0.02
Log Output Level= 0
Friction Slope Method= 1
Unsteady Friction Slope Method= 2
Unsteady Bridges Friction Slope Method= 1
Parabolic Critical Depth
Global Vel Dist= 0 , 0 , 0
Global Log Level= 0
CheckData=True
Encroach Param=-1 ,0,0, 0
Mapping Interval=1HOUR
Computation Time Step Use Courant=        0
Computation Time Step Use Time Series=    0
Computation Time Step Count To Double=0
Computation Time Step Max Doubling=0
Computation Time Step Max Halving=0
Computation Time Step Residence Courant=0
Run HTab= 0
Run UNet= 0
Run Sediment= 0
Run PostProcess= 0
Run WQNet= 0
Run RASMapper=-1
UNET Theta= 0
UNET Theta Warmup= 0
UNET ZTol= 0
UNET ZSATol= 0
UNET MxIter= 0
UNET Max Iter WO Improvement= 0
UNET MaxInSteps= 0
UNET DtIC= 0
UNET DtMin= 0
UNET MaxCRTS= 0
UNET WFStab= 0
UNET SFStab= 0
UNET WFX= 1
UNET SFX= 1
UNET Gravity=32.174
UNET 1D Methodology=Finite Difference
UNET DSS MLevel= 1
UNET Pardiso=0
UNET DZMax Abort= 0
UNET Use Existing IB Tables= 0
UNET Froude Reduction=False
UNET Froude Limit= 0
UNET Froude Power= 0
UNET D1 Cores= 0
UNET WindReference=Eulerian
UNET WindDragFormulation=Hsu (1988)
UNET D2 Coriolis=0
UNET D2 Cores= 0
UNET D2 Theta= 1
UNET D2 Theta Warmup= 1
UNET D2 Z Tol= 0.01
UNET D2 Volume Tol= 0.01
UNET D2 Max Iterations= 20
UNET D2 Equation= 0
UNET D2 RampUpFraction=0.1
UNET D2 TimeSlices= 1
UNET D2 Turbulence Formulation=Non-Conservative (original)
UNET D2 Eddy Viscosity=0.3
UNET D2 Transverse Eddy Viscosity=0.1
UNET D2 Smagorinsky Mixing=0
UNET D2 BCVolumeCheck=0
UNET D2 Cores=0
UNET D2 SolverType=PARDISO (Direct)
UNET D2 Minimum Iterations= 2147483647
UNET D2 Maximum Iterations= 2147483647
UNET D2 Restart Number= 10
UNET D2 Relaxation Coeff=1.3
UNET D2 SOR Precondition Iterations= 10
UNET D2 ILUT Maximum Fill= 8
UNET D2 ILUT Tolerance=1E-08
UNET D1D2 MaxIter= 0
UNET D1D2 ZTol=0.01
UNET D1D2 QTol=0.1
UNET D1D2 MinQTol=1
Write IC File= 0
Write IC File at Fixed DateTime=0
Write IC File at Sim End=0
Echo Input=False
Echo Parameters=False
Echo Output=False
Write Detailed= 0
HDF Write Warmup=0
HDF Write Time Slices=0
HDF Flush=0
HDF Compression= 1
HDF Chunk Size= 1
HDF Spatial Parts= 1
HDF Use Max Rows=0
HDF Fixed Rows= 1
Calibration Method= 0
Calibration Iterations= 20
Calibration Max Change=0.05
Calibration Tolerance=0.2
Calibration Maximum=1.5
Calibration Minimum=0.5
Calibration Optimization Method= 1
WQ AD Non Conservative
WQ ULTIMATE=-1
WQ Max Comp Step=1HOUR
WQ Output Interval=15MIN
WQ Output Selected Increments= 0
WQ Output face flow=0
WQ Output face velocity=0
WQ Output face area=0
WQ Output face dispersion=0
WQ Output cell volume=0
WQ Output cell surface area=0
WQ Output cell continuity=0
WQ Output cumulative cell continuity=0
WQ Output face conc=0
WQ Output face dconc_dx=0
WQ Output face courant=0
WQ Output face peclet=0
WQ Output face adv mass=0
WQ Output face disp mass=0
WQ Output cell mass=0
WQ Output cell source sink temp=0
WQ Output nsm pathways=0
WQ Output nsm derived pathways=0
WQ Create Restart=0
WQ Fixed Restart=0
WQ System Summary=0
WQ Write To DSS=0
Sorting and Armoring Iterations= 10
XS Update Threshold= 0.02
Bed Roughness Predictor= 0
Hydraulics Update Threshold= 0.02
Energy Slope Method= 1
Volume Change Method= 1
Sediment Retention Method= 0
Sediment TS Multiplier= 1
Warm Up Method= 0
XS Weighting Method= 0
Number of US Weighted Cross Sections= 1
Number of DS Weighted Cross Sections= 1
Upstream XS Weight=0
Main XS Weight=1
Downstream XS Weight=0
Number of DS XS's Weighted with US Boundary= 1
Upstream Boundary Weight= 1
Weight of XSs Associated with US Boundary= 0
Number of US XS's Weighted with DS Boundary= 1
Downstream Boundary Weight= 0.5
Weight of XSs Associated with DS Boundary= 0.5
Percentile Method= 0
Sediment Output Level= 3
Mass or Volume Output= 0
Output Increment Type= 1
Profile and TS Output Increment= 1
Transport Output Increment 1
XS Output Flag= 0
XS Output Increment= 10
Read HDF5 Sediment Hotstart= 0
Sediment Hotstart Type= 0
Write Gradation File= 0
Read Gradation Hotstart= 0
Write HDF5 File= 1
Write Binary Output= 1
Write DSS Sediment File= 0
DSS Sediment Output Type= 1
SV Curve= 0
Specific Gage Flag= 0
Subcell Erosion Methods= 0
Subcell Deposition Methods= 0
Advection Scheme= 1
Matrix Solver= 0
Implicit Weighting Factor= 1
Maximum Outer Loop Convergence Iterations= 5
Convergence Maximum Absolute= 0.001
Convergence RMSE= 0.0001
Grain Fractions Max Abs Error= 0.001
Max Subgrid Regions= 1
Max Subgrid Length Scale= 3.402823E+38
Initial Layer Thickness= 3.402823E+38
Min Layer Thickness= 3.402823E+38
Max Layer Thickness= 3.402823E+38
Number of Layers= 5

--- MFRFBUCKRV.f01 (steady flow) ---

Flow Title=Flow
Program Version=6.20
Number of Profiles= 1
Profile Names=P100yr
River Rch & RM=MFRFBUCKRV,Main            ,18264
     331
River Rch & RM=MFRFBUCKRV,Main            ,17027
     370
River Rch & RM=MFRFBUCKRV,Main            ,15126
     413
River Rch & RM=MFRFBUCKRV,Main            ,12734
     562
River Rch & RM=MFRFBUCKRV,Main            ,10922
     673
River Rch & RM=MFRFBUCKRV,Main            ,6621
     935
River Rch & RM=MFRFBUCKRV,Main            ,4653
    1200
River Rch & RM=MFRFBUCKRV,Main            ,3386
    1380
River Rch & RM=MFRFBUCKRV,Main            ,2188
    3950
Boundary for River Rch & Prof#=MFRFBUCKRV,Main            , 1
Up Type= 0
Dn Type= 3
Dn Slope=0.013817
DSS Import GetInterval= 0
DSS Import GetPeak= 0
DSS Import FillOption= 0

--- MFRFBUCKRV.g01 (geometry) ---

Geom Title=Geometry
Program Version=6.20

River Reach=MFRFBUCKRV      ,Main
Reach XY= 30
     2190811.395      623716.118      2191079.19      624699.191
     2191001.568      625342.937     2191535.851      626107.233
     2191610.462      626503.288     2191509.729      627368.649
     2191244.652      627592.437     2191137.368      628335.612
2189970.82642183628601.655890874     2189559.951      628991.996
     2189601.328      629153.493     2189346.951      629203.676
     2189307.537      629453.158     2188775.734      629826.548
     2188700.076       630343.26     2188229.738      630328.559
     2188034.291      630656.949      2187701.82      630573.771
     2187222.353      630946.179     2187102.554      630820.761
     2186642.052      630899.924     2186272.478      631569.824
     2186393.131      632014.788     2186110.118       632516.58
2186271.78680936632871.934128596     2186153.948      633289.545
     2186429.631      633719.415     2186033.054      635371.428
     2186105.805      635749.357     2186636.187      636319.649

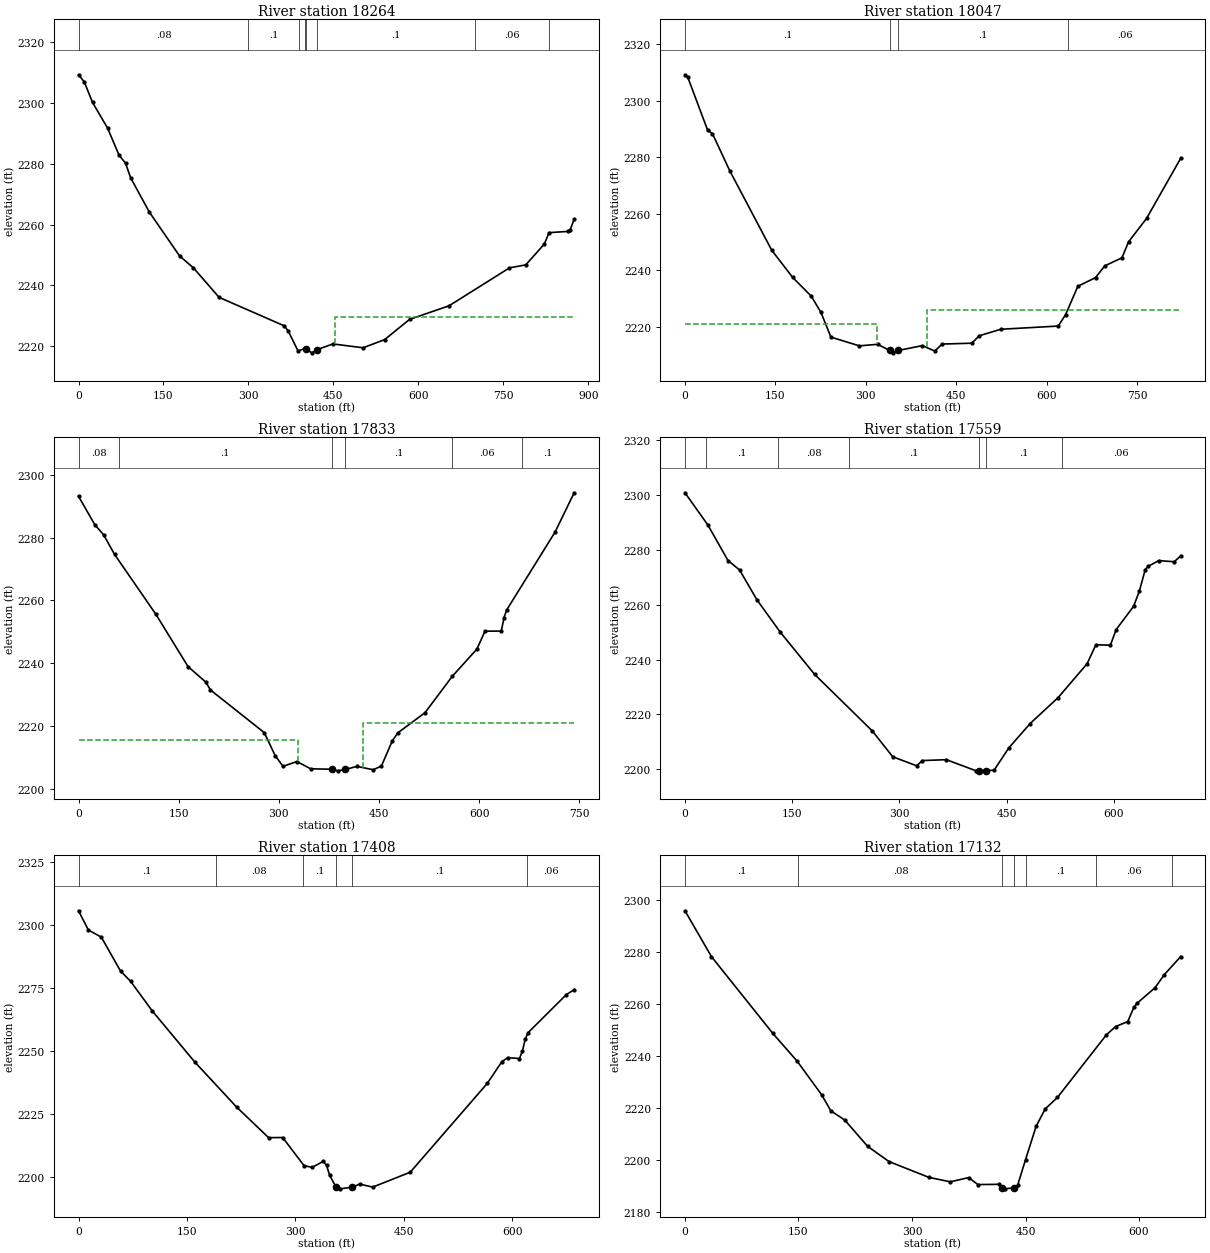
Type RM Length L Ch R = 1 ,18264   ,215.9,216.7,217.4
XS GIS Cut Line= 2
2190414.26285371623818.7115698922191267.51107226  623623.7834543
#Sta/Elev= 30
       0 2309.18    10.2 2306.84    24.8 2300.08    51.2 2291.72    71.7 2282.73
      83 2280.16    92.2 2275.29   125.1 2264.09   178.4 2249.69     203 2245.77
   248.1  2236.1     363 2226.76   370.3 2225.06   387.6 2218.48     400  2219.3
     402 2218.99   412.3 2217.87   421.3 2218.92   449.2 2220.79   502.5 2219.53
   540.6 2222.22   584.6 2228.86   654.2 2233.31     761 2245.78   789.7 2246.75
   822.6 2253.61   830.8 2257.34   864.6 2257.75   867.7  2258.1   875.2 2261.68
#Mann= 8 ,-1,0
       0     .08       0     300      .1       0     390     .08       0
     400      .1       0     402    .045       0   421.3      .1       0
     700     .06       0     830      .1       0
#XS Ineff= 2 , 0
                          453.43         2229.79
Permanent Ineff=
       F       F
Bank Sta=402,421.3
XS Rating Curve= 0 ,0
Exp/Cntr(USF)=0,0
Exp/Cntr=0.3,0.1

Type RM Length L Ch R = 1 ,18047   ,214,214.4,216.9
XS GIS Cut Line= 3
2190479.62797032624013.6396854842191080.75359625623880.574983822
2191283.85235142623917.926479026
#Sta/Elev= 30
       0 2309.26     4.7 2308.36    37.4 2289.74    45.6  2288.4    74.3 2275.28
   143.9 2247.16   178.6 2237.54   209.5  2230.9   225.6 2225.13   242.1  2216.4
   289.3 2213.31   319.5 2213.86   339.82211.676   344.7 2210.84   353.8 2211.68
   393.9  2213.4   414.3 2211.46   426.6 2213.95   475.8 2214.25   488.1 2216.89
   524.1 2219.19   619.2 2220.32   631.4 2224.38   651.7  2234.4     681 2237.47
   696.4 2241.63   724.9 2244.48   735.9 2250.17   765.6 2258.39   822.2 2279.67
#Mann= 4 ,-1,0
       0      .1       0   339.8    .045       0   353.8      .1       0
  635.68     .06       0
#XS Ineff= 2 , 0
          319.13  2220.9  400.73         2225.96
Permanent Ineff=
       F       F
Bank Sta=339.8,353.8
XS Rating Curve= 0 ,0
Exp/Cntr(USF)=0,0
Exp/Cntr=0.3,0.1

Type RM Length L Ch R = 1 ,17833   ,270.5,273.8,275.2
XS GIS Cut Line= 3
2190547.32755538624196.8954588252191169.46339736624072.001396739
2191276.84894606 624081.33927054
#Sta/Elev= 30
       0 2293.17    24.3 2284.13    37.6 2280.89    53.9 2274.67     116 2255.53
   164.1  2238.9   190.8 2233.95   197.5  2231.5   278.3 2217.87   294.6 2210.53
   306.3 2207.15   327.2 2208.69   347.6 2206.37   379.2 2206.23   388.4 2205.72
   399.6 2206.16     417 2207.14   441.5 2206.06   453.7 2207.28     470 2215.28
   478.2 2217.81     519 2224.25   559.8 2235.84   596.5 2244.45   608.8  2250.2
   633.2 2250.23   637.3 2254.55   641.3 2256.98   713.6 2281.72   742.3 2294.27
#Mann= 6 ,-1,0
       0     .08       0      60      .1       0   379.2    .045       0
   399.6      .1       0     560     .06       0  664.55      .1       0
#XS Ineff= 2 , 0
          328.09 2215.52   425.5         2220.84
Permanent Ineff=
       F       F
Bank Sta=379.2,399.6
XS Rating Curve= 0 ,0
Exp/Cntr(USF)=0,0
Exp/Cntr=0.3,0.1

Type RM Length L Ch R = 1 ,17559   ,157.2,150.9,141.1
XS GIS Cut Line= 4
  2190576.508411624352.137610763 2190860.1463277 624312.45164711
2191014.22124542624357.9737818892191257.00596424624315.953349785
#Sta/Elev= 30
       0 2300.86      32 2289.12    60.2 2276.14    76.4 2272.71   100.6 2261.85
   132.9 2250.15   181.4 2234.62   262.2 2213.95   290.6 2204.58     324 2201.28
   332.3 2203.18   365.7  2203.5   407.4 2199.43   411.6 2199.46   421.5 2199.55
   432.4 2199.63   453.1 2207.79   482.8 2216.65   522.1 2226.15   562.7 2238.53
   574.9 2245.41   595.2 2245.26   603.3 2250.96   627.7 2259.45   635.8 2265.04
   643.9 2272.75     648 2274.02   662.8 2276.11   684.5 2275.71   693.5  2277.8
#Mann= 7 ,-1,0
       0     .08       0      30      .1       0     130     .08       0
     230      .1       0   411.6    .045       0   421.5      .1       0
  527.06     .06       0
Bank Sta=411.6,421.5
XS Rating Curve= 0 ,0
Exp/Cntr(USF)=0,0
Exp/Cntr=0.3,0.1

Type RM Length L Ch R = 1 ,17408   ,270.4,276.1,279.5
XS GIS Cut Line= 3
2190627.86671691 624653.284040842191050.40550639624446.683582997
2191262.84213536624410.499322019
#Sta/Elev= 30
       0 2305.47    13.7 2297.82    31.5 2295.04    58.2 2281.54    72.1 2277.49
     102 2265.77   160.6 2245.59   218.6 2227.67     263  2215.5   282.5 2215.55
     312 2204.42   323.3 2203.69   338.7 2206.14   343.2 2204.49   347.6  2200.5
   356.5 2195.79   362.1  2195.2   378.8 2195.85   389.1 2197.09     407 2195.88
     459 2201.79   565.5 2236.99   585.8 2245.64   593.9 2247.24   610.1 2246.88
   614.2 2249.82   618.2  2254.7   622.2 2257.17     675 2272.23   685.8  2274.2
#Mann= 6 ,-1,0
       0      .1       0     190     .08       0     310      .1       0
   356.5    .045       0   378.8      .1       0  620.34     .06       0
Bank Sta=356.5,378.8
XS Rating Curve= 0 ,0
Exp/Cntr(USF)=0,0
Exp/Cntr=0.3,0.1

Type RM Length L Ch R = 1 ,17132   ,104.6,105.2,105.1
XS GIS Cut Line= 3
2190653.54586986624667.2908515412191121.60679413624738.492139272
2191301.36086479 624712.81298632
#Sta/Elev= 30
       0 2295.83      35 2278.22   115.9 2248.81   148.3 2238.05   180.7 2225.13
   192.8 2218.99   211.2 2215.46   241.4 2205.36   269.7 2199.51   322.3 2193.46
   350.6 2191.74   374.9 2193.37     387  2190.7   415.4 2190.78   419.4 2189.44
   423.4 2189.05   435.1 2189.49   439.6 2190.43     450 2200.22     464 2213.04
     476 2219.74   492.2 2224.15   556.9 2248.19     569 2251.37   585.1 2253.27
   593.2 2258.73   597.5 2260.32   621.1 2266.26   633.6 2271.36     655 2278.22
#Mann= 7 ,-1,0
       0      .1       0     150     .08       0   419.4    .045       0
   435.1     .08       0     450      .1       0  543.45     .06       0
  643.45      .1       0
Bank Sta=419.4,435.1
XS Rating Curve= 0 ,0
Exp/Cntr(USF)=0,0
Exp/Cntr=0.3,0.1

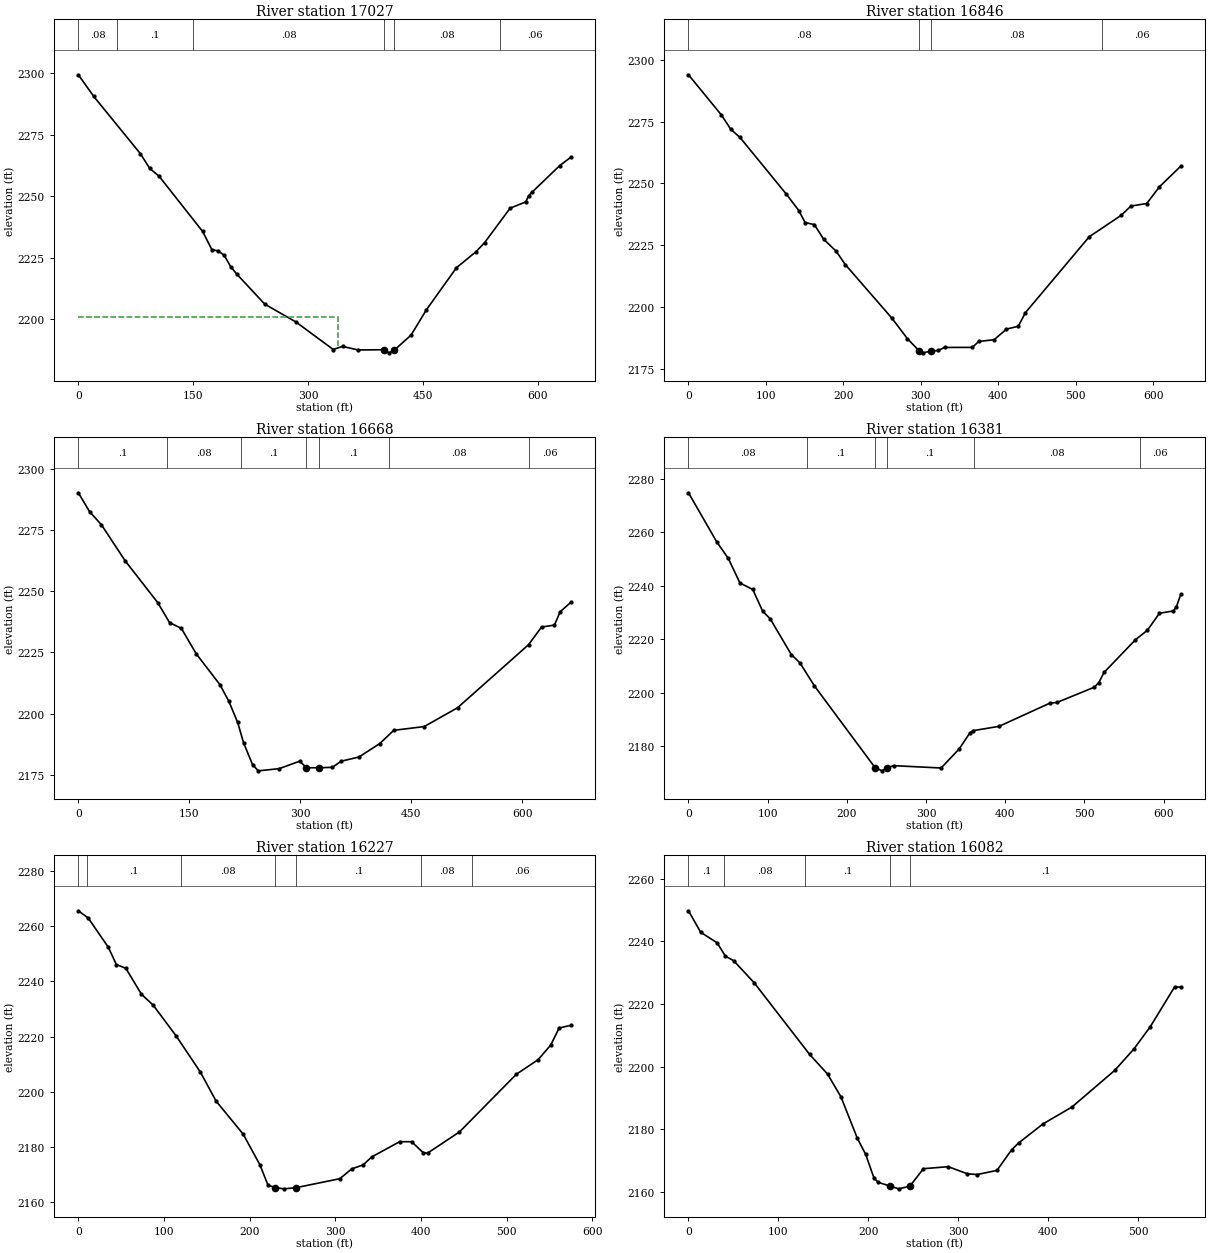
Type RM Length L Ch R = 1 ,17027   ,181.6,180.3,178.2
XS GIS Cut Line= 3
2190652.37863564624763.0040579992191076.08465935624837.707048406
2191286.18681987624805.024490103
#Sta/Elev= 30
       0 2299.24    20.1 2290.46      81 2267.24    93.2 2261.28   105.4 2258.09
   162.3 2235.69   174.4 2228.28   182.6 2227.81   190.7 2225.94   198.8 2221.44
   206.9 2218.39   243.4  2206.2   284.1 2198.97   332.9 2187.79     345 2189.05
   365.3 2187.61   398.8  2187.7     406 2186.44   412.6 2187.55   434.4  2193.6
   454.6 2203.94   493.8 2220.97   519.4 2227.49   530.4  2231.1   563.9 2245.13
   584.2 2247.66   588.2 2250.19   592.3 2251.55   628.7 2262.42   642.9 2265.73
#Mann= 6 ,-1,0
       0     .08       0      50      .1       0     150     .08       0
   398.8    .045       0   412.6     .08       0  550.24     .06       0
#XS Ineff= 2 , 0
          339.16  2200.9
Permanent Ineff=
       F       F
Bank Sta=398.8,412.6
XS Rating Curve= 0 ,0
Exp/Cntr(USF)=0,0
Exp/Cntr=0.3,0.1

Type RM Length L Ch R = 1 ,16846   ,177,177.8,177.3
XS GIS Cut Line= 3
2190661.71650944624991.7819661192191085.42253315624984.778560769
2191290.85575677624933.420254864
#Sta/Elev= 30
       0  2293.9    42.5 2277.65    54.5  2271.9    66.5 2268.56   126.5 2245.59
   142.5    2239   150.5 2234.19   162.5 2233.36   174.5 2227.45   190.5 2222.64
   202.5 2217.17   262.5 2195.58   282.5  2187.3   297.92182.284   302.5 2181.54
   312.82182.234   322.5 2182.49   330.5 2183.73   366.5 2183.74   374.5 2186.13
   394.5 2186.84   410.5 2191.12   425.7 2192.28   434.8 2197.73   517.3 2228.45
   558.5  2237.1     571 2240.84   591.5 2241.88     608 2248.66   635.5 2256.99
#Mann= 4 ,-1,0
       0     .08       0   297.9    .045       0   312.8     .08       0
  533.76     .06       0
Bank Sta=297.9,312.8
XS Rating Curve= 0 ,0
Exp/Cntr(USF)=0,0
Exp/Cntr=0.3,0.1

Type RM Length L Ch R = 1 ,16668   ,288.5,287.8,282.5
XS GIS Cut Line= 3
2190676.89055436 625168.034334112191176.46680271625154.027523409
2191328.20725197625087.495172578
#Sta/Elev= 30
       0 2290.19    15.3 2282.44    31.3 2277.08    63.3 2262.39   107.3 2245.32
   123.3 2237.16   139.3 2234.77   159.3 2224.43   191.4 2211.79   203.4 2205.03
   215.4 2196.35   223.4    2188   235.6 2179.05   243.3 2176.59   271.4 2177.48
   299.4 2180.55   308.3 2177.85   325.7 2177.85   343.4 2178.03   355.4 2180.53
   379.4 2182.25   407.4 2187.72   426.4 2193.15   467.5 2194.67   512.6 2202.36
   608.6 2228.13   626.1 2235.32   643.6 2236.14   651.3 2241.56   665.5 2245.37
#Mann= 7 ,-1,0
       0      .1       0     120     .08       0     220      .1       0
   308.3    .045       0   325.7      .1       0     420     .08       0
  609.77     .06       0
Bank Sta=308.3,325.7
XS Rating Curve= 0 ,0
Exp/Cntr(USF)=0,0
Exp/Cntr=0.3,0.1

Type RM Length L Ch R = 1 ,16381   ,153.1,153.4,153.7
XS GIS Cut Line= 2
2190797.11567955625478.5186379872191341.04682845625177.372207911
#Sta/Elev= 30
       0 2274.83    35.6 2256.47    50.3 2250.22      65 2241.03    81.2 2238.61
    93.6 2230.51   103.3 2227.57   129.8 2214.25   140.7 2211.14   158.9 2202.54
   235.7 2171.84   244.5 2170.68   250.4 2171.78   259.3 2172.62     319 2171.74
   341.8 2178.87   355.6    2185   359.3 2185.73   392.1 2187.34   456.1    2196
   465.4  2196.3   512.3 2201.98   518.2 2203.73   524.7 2207.52   564.3 2219.75
   579.6 2223.36   594.7 2229.69   612.4 2230.58   616.2 2232.14   621.7 2236.84
#Mann= 6 ,-1,0
       0     .08       0     150      .1       0   235.7    .045       0
   250.4      .1       0     360     .08       0     570     .06       0
Bank Sta=235.7,250.4
XS Rating Curve= 0 ,0
Exp/Cntr(USF)=0,0
Exp/Cntr=0.3,0.1

Type RM Length L Ch R = 1 ,16227   ,145.3,145,145.7
XS GIS Cut Line= 2
2190893.99612023625606.9144027482191387.73619745625312.771378023
#Sta/Elev= 30
       0 2265.61    11.6 2262.96    35.1 2252.32    44.4 2246.09    55.4 2244.77
    73.7 2235.31    87.5 2231.33   114.3 2220.15   142.2 2207.22   160.8 2196.57
   192.5 2184.55   212.1 2173.37   221.4 2166.06     230 2165.19     240 2164.74
     254 2165.15   305.2 2168.42   319.1 2171.96   332.6 2173.45   342.4  2176.3
     375 2181.83     389 2181.84   402.6 2177.86   407.6 2177.68   444.9 2185.38
   511.4 2206.33   536.8 2211.61   551.4 2216.89   561.3  2223.1   574.7 2224.04
#Mann= 7 ,-1,0
       0     .08       0      10      .1       0     120     .08       0
     230    .045       0     254      .1       0     400     .08       0
     460     .06       0
Bank Sta=230,254
XS Rating Curve= 0 ,0
Exp/Cntr(USF)=0,0
Exp/Cntr=0.3,0.1

Type RM Length L Ch R = 1 ,16082   ,143.2,147.3,151
XS GIS Cut Line= 2
2190980.37145289625716.6344199082191457.77025096625449.337782359
#Sta/Elev= 30
       0 2249.73    13.5 2242.89    31.8 2239.51      41 2235.27    50.2 2233.81
    73.1 2226.73   134.6 2203.92   154.5 2197.67   169.4  2190.4   187.5 2177.27
   196.9 2172.05   206.1 2164.53   210.7 2163.14   224.4  2161.9   233.6 2161.05
     2462161.903   261.1 2167.47   288.6 2168.12     310 2165.84   320.7 2165.61
   342.8 2166.93   359.1  2173.5   366.8 2175.67     394 2181.76   426.1 2187.14
   473.8 2198.86   494.9 2205.63   513.2 2212.77   540.2 2225.45   547.1 2225.39
#Mann= 5 ,-1,0
       0      .1       0      40     .08       0     130      .1       0
   224.4    .045       0     246      .1       0
Bank Sta=224.4,246
XS Rating Curve= 0 ,0
Exp/Cntr(USF)=0,0
Exp/Cntr=0.3,0.1

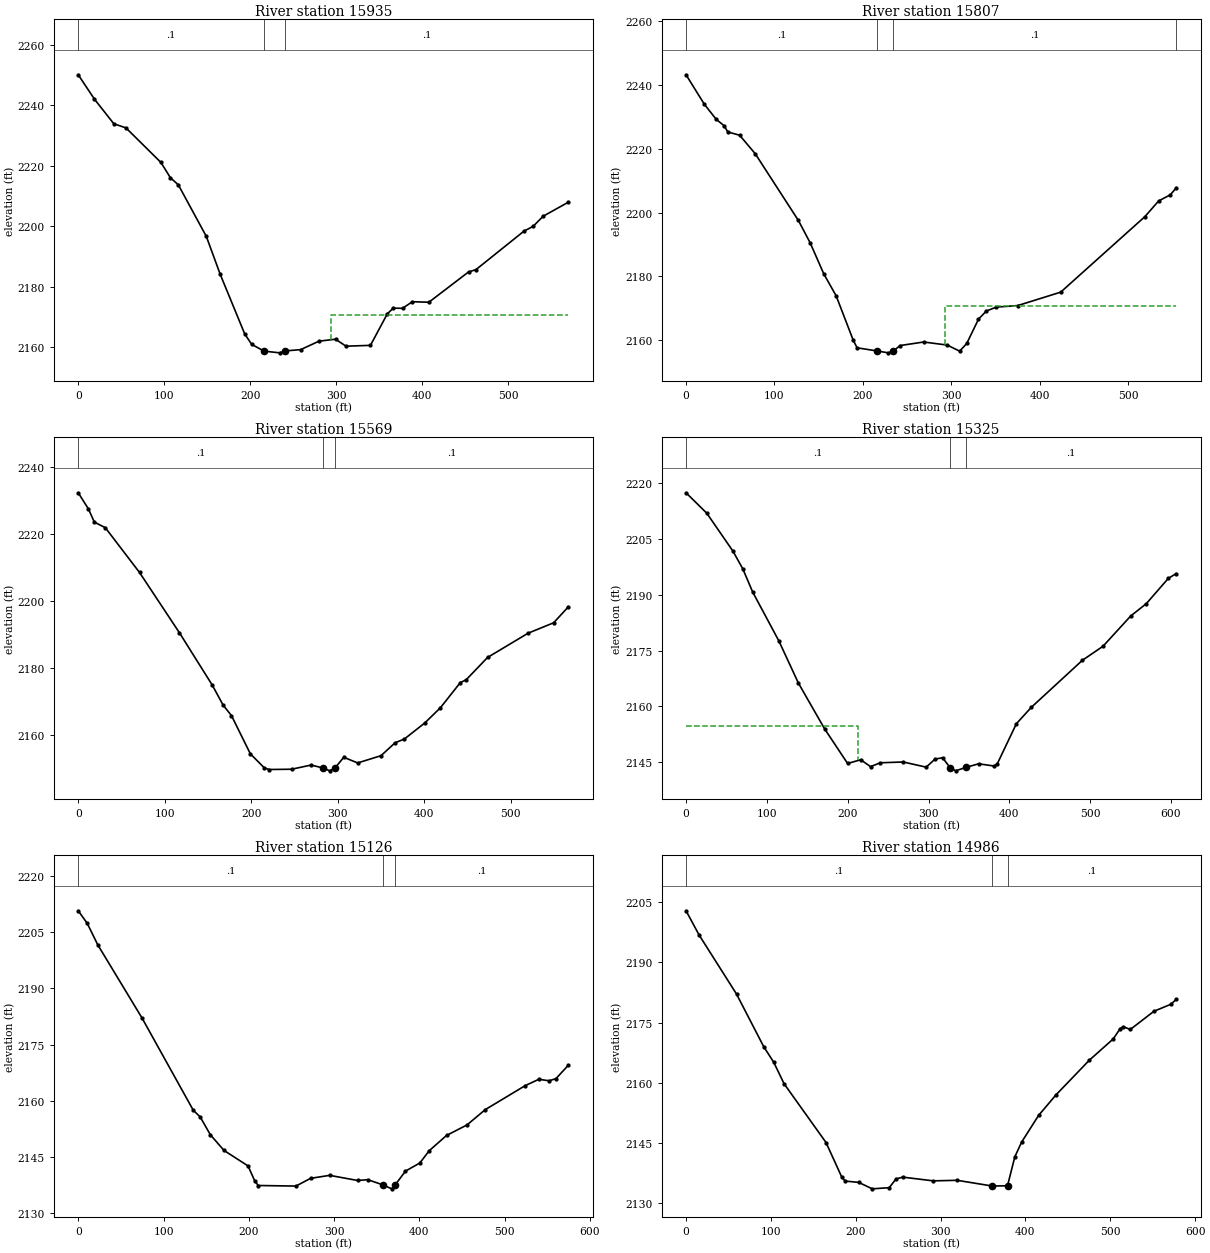
Type RM Length L Ch R = 1 ,15935   ,132.2,128,125.4
XS GIS Cut Line= 3
2191009.55230852625778.497833838 2191376.0638552625714.299951458
2191540.64388094625604.579934298
#Sta/Elev= 30
       0 2250.08    18.9    2242    41.4 2233.89    55.5 2232.53    96.1 2221.12
   107.1 2216.09   116.4 2213.69   148.9 2196.68   165.1 2184.11   193.5 2164.48
   201.6 2161.02     2162158.778   234.1 2158.21   240.6 2158.85   258.5 2159.26
   279.9 2162.07   299.1 2162.71   311.3 2160.41   339.7 2160.68   359.3 2171.09
   366.2 2172.98     377 2172.92   388.5 2175.11   407.6 2174.92   453.7 2184.93
   462.4 2185.71   518.3 2198.45   528.7 2199.97   540.5 2203.35   569.9    2208
#Mann= 3 ,-1,0
       0      .1       0     216    .045       0   240.6      .1       0
#XS Ineff= 2 , 0
                          293.72         2170.62
Permanent Ineff=
       F       F
Bank Sta=216,240.6
XS Rating Curve= 0 ,0
Exp/Cntr(USF)=0,0
Exp/Cntr=0.3,0.1

Type RM Length L Ch R = 1 ,15807   ,240,237.9,234.4
XS GIS Cut Line= 2
2191085.42253315625950.0812649282191586.16601572625711.965483007
#Sta/Elev= 30
       0 2243.25    20.8 2233.97    34.1 2229.29    42.9  2227.3    47.3 2225.31
    60.6 2224.29    78.3 2218.47   127.1 2197.54   140.4 2190.54   155.8  2180.8
   169.8 2173.91   189.1 2159.99   193.5  2157.6   216.3  2156.6   228.9 2156.02
   233.9 2156.46   242.2 2158.31   268.8 2159.42   295.4 2158.46   309.5 2156.55
   317.5 2158.95   330.8 2166.58   339.7 2169.14     351 2170.37   375.1 2170.84
   423.8 2175.06   519.1 2198.77   534.6 2203.68   547.8 2205.59   554.5  2207.8
#Mann= 4 ,-1,0
       0      .1       0   216.3    .045       0   233.9      .1       0
  554.48     .06       0
#XS Ineff= 2 , 0
                          293.29         2170.83
Permanent Ineff=
       F       F
Bank Sta=216.3,233.9
XS Rating Curve= 0 ,0
Exp/Cntr(USF)=0,0
Exp/Cntr=0.3,0.1

Type RM Length L Ch R = 1 ,15569   ,240.1,244.3,249.9
XS GIS Cut Line= 3
2191172.96510003626141.5076778452191353.88640492626081.978732365
2191632.85538472625829.856139743
#Sta/Elev= 30
       0 2232.36    11.8 2227.52    18.6  2223.6    31.3 2221.93    70.8 2208.56
   116.9 2190.56     155 2174.86   167.4 2168.94   177.1 2165.79   198.9 2154.38
   215.1 2150.17   220.5  2149.7   246.5 2149.78   269.1 2151.03   283.3 2150.13
   290.6  2149.3   296.72150.135   306.8 2153.35   322.9 2151.66   349.9 2153.83
   366.1 2157.67   376.9 2158.81   400.5 2163.61   418.4 2168.11   441.6 2175.68
   448.2 2176.48     473 2183.17   519.8 2190.41   549.4 2193.53   566.5 2198.33
#Mann= 3 ,-1,0
       0      .1       0   283.3    .045       0   296.7      .1       0
Bank Sta=283.3,296.7
XS Rating Curve= 0 ,0
Exp/Cntr(USF)=0,0
Exp/Cntr=0.3,0.1

Type RM Length L Ch R = 1 ,15325   ,198.2,198.7,198.6
XS GIS Cut Line= 3
2191206.81489256 626257.063866132191597.83835797626194.033217974
2191770.58902328626073.808092789
#Sta/Elev= 30
       0 2217.41    25.7 2211.91    58.1  2201.7    70.3 2196.93    82.4 2190.75
   114.8  2177.6   139.1 2166.21   171.5 2153.92   199.9 2144.63   216.1 2145.63
   228.3 2143.78   240.4 2144.82   268.8 2145.03   297.1 2143.64   308.1 2145.81
   317.4 2146.17   326.72143.502   333.6 2142.65   345.8 2143.55     362 2144.54
   381.4 2143.94   384.9 2144.46   408.7 2155.32   427.1 2159.71   490.3 2172.36
   515.9 2176.15     550 2184.25   569.5 2187.61   596.6 2194.38   606.5  2195.7
#Mann= 3 ,-1,0
       0      .1       0   326.7    .045       0   345.8      .1       0
#XS Ineff= 2 , 0
          212.93 2154.78
Permanent Ineff=
       F       F
Bank Sta=326.7,345.8
XS Rating Curve= 0 ,0
Exp/Cntr(USF)=0,0
Exp/Cntr=0.3,0.1

Type RM Length L Ch R = 1 ,15126   ,139.1,139.9,140.5
XS GIS Cut Line= 2
2191233.66127974626419.3094234192191806.77328426626374.954522865
#Sta/Elev= 30
       0  2210.7    10.5 2207.37    22.9 2201.61    74.7 2182.12   134.9 2157.47
   142.9 2155.72     155 2150.91     171 2146.74   199.1 2142.62   207.1 2138.56
   211.1  2137.4   255.3 2137.25   272.4 2139.31   294.8 2140.11   327.5 2138.74
   339.5 2138.95     357 2137.59   367.6 2136.51   371.6 2137.56   383.7 2141.24
   400.5  2143.4   411.7 2146.72   431.8 2150.75   455.9 2153.57   477.2 2157.64
   524.1 2164.05   540.1 2165.74   552.2 2165.34   560.2 2165.93   574.8 2169.53
#Mann= 3 ,-1,0
       0      .1       0     357    .045       0   371.6      .1       0
Bank Sta=357,371.6
XS Rating Curve= 0 ,0
Exp/Cntr(USF)=0,0
Exp/Cntr=0.3,0.1

Type RM Length L Ch R = 1 ,14986   ,135.7,136.7,136.9
XS GIS Cut Line= 2
2191240.66468509626531.3639090292191818.44562651626529.029440579
#Sta/Elev= 30
       0 2202.89    15.5 2196.81    59.5 2182.11    91.5    2169   103.5 2165.03
   115.5 2159.74     165 2145.05   183.5 2136.45   187.5 2135.43   203.5  2135.1
   219.5 2133.49   239.5 2133.78   247.5 2135.97   255.5 2136.41   291.5 2135.48
   319.5 2135.62   360.72134.198   378.9 2134.25   387.5 2141.46   395.5 2145.14
   415.5  2151.8   435.9 2156.91   475.5 2165.63   503.4 2170.88   511.5 2173.41
   515.5 2173.96   523.6 2173.26   551.5 2177.81   571.5 2179.56   577.8 2180.78
#Mann= 3 ,-1,0
       0      .1       0   360.7    .045       0   378.9      .1       0
Bank Sta=360.7,378.9
XS Rating Curve= 0 ,0
Exp/Cntr(USF)=0,0
Exp/Cntr=0.3,0.1

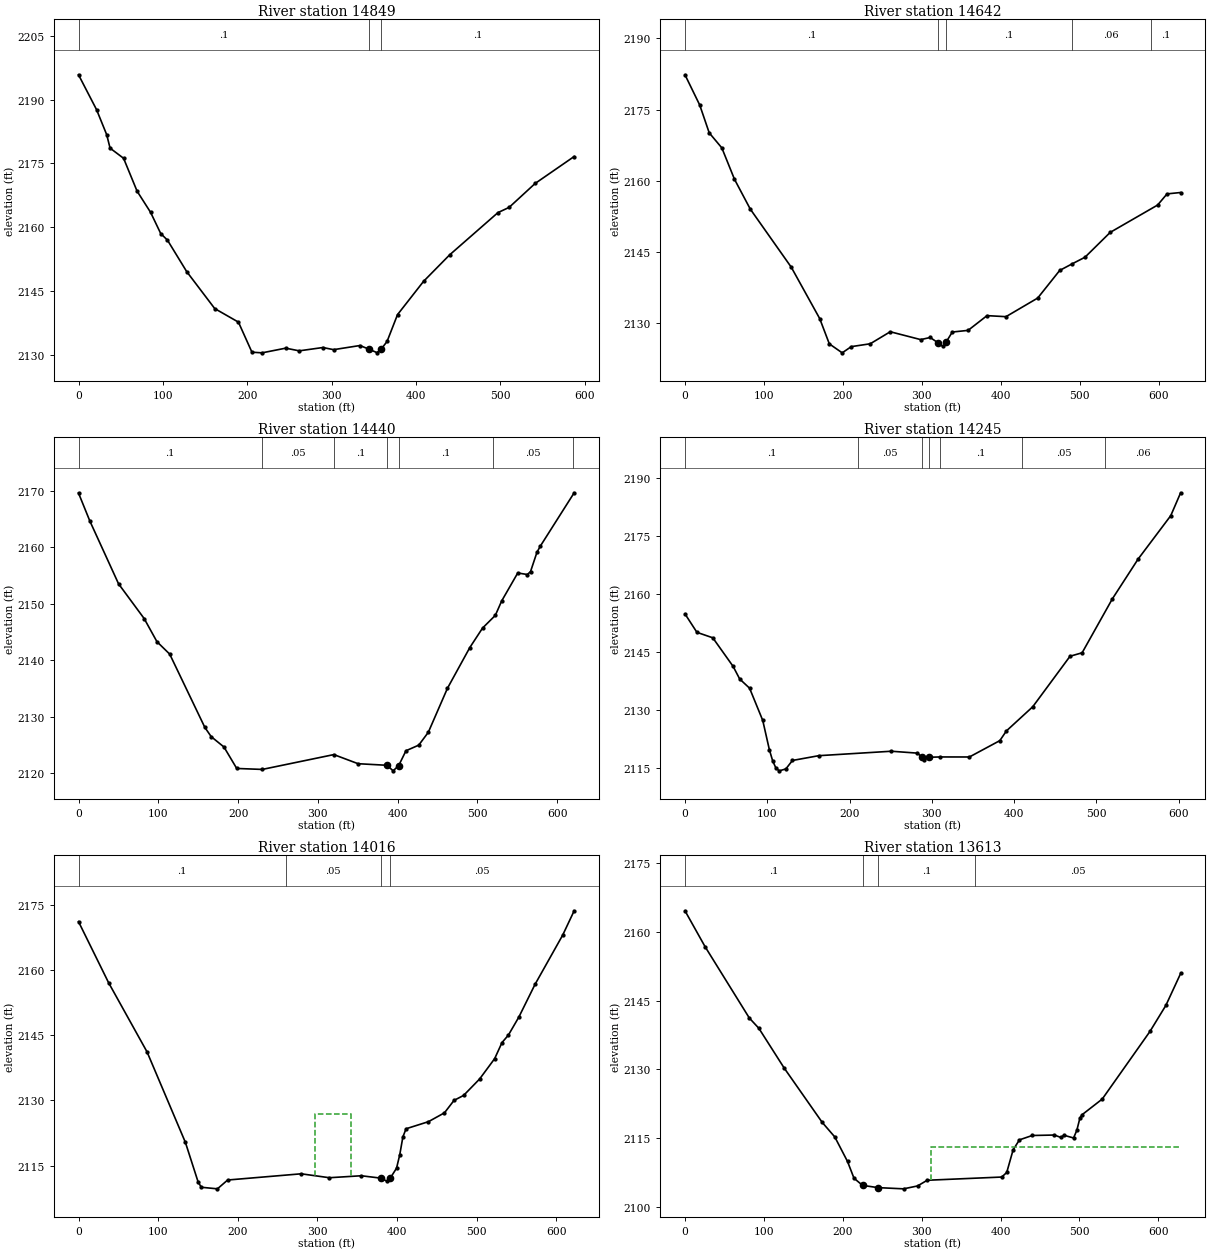
Type RM Length L Ch R = 1 ,14849   ,206.4,207.3,207.2
XS GIS Cut Line= 3
2191234.82851396626651.5890342152191608.34346599626664.428610691
2191802.10434736626574.551575358
#Sta/Elev= 30
       0 2195.83    21.4 2187.62    33.4 2181.74    37.4 2178.58    53.4 2176.19
    69.4 2168.46    85.4 2163.48    97.4  2158.5   105.4 2156.94   128.2 2149.54
   161.4 2140.85   189.5 2137.66   205.5 2130.59   217.5 2130.44   245.5 2131.54
   261.5 2130.91   289.5 2131.69   302.3 2131.19   333.5 2132.16   343.8 2131.33
   353.6 2130.49   358.8 2131.35   365.6 2133.12     378 2139.43   408.8 2147.24
   439.7 2153.47     497 2163.42   510.2 2164.64   541.1 2170.28   587.3 2176.61
#Mann= 3 ,-1,0
       0      .1       0   343.8    .045       0   358.8      .1       0
Bank Sta=343.8,358.8
XS Rating Curve= 0 ,0
Exp/Cntr(USF)=0,0
Exp/Cntr=0.3,0.1

Type RM Length L Ch R = 1 ,14642   ,200.5,201.8,201.8
XS GIS Cut Line= 2
2191197.47701876626819.6707626292191825.44903186626810.332888828
#Sta/Elev= 30
       0 2182.33    18.7 2175.94    30.7 2170.08    46.7  2166.9    62.7 2160.29
    82.7    2154   134.7 2141.72   170.7 2130.89   182.9 2125.55   199.2 2123.66
   210.7 2124.97   234.7 2125.57   260.1 2128.11   298.7 2126.45   310.7  2126.9
   320.5 2125.79   326.7 2125.02   330.7 2125.89   338.7 2128.05   358.7  2128.4
   382.7 2131.51   406.7 2131.29   446.9 2135.22   474.8 2141.05     490 2142.39
   506.8 2143.83   538.8 2149.08   598.8 2154.84   610.8  2157.2     628 2157.49
#Mann= 5 ,-1,0
       0      .1       0   320.5    .045       0   330.7      .1       0
     490     .06       0     590      .1       0
Bank Sta=320.5,330.7
XS Rating Curve= 0 ,0
Exp/Cntr(USF)=0,0
Exp/Cntr=0.3,0.1

Type RM Length L Ch R = 1 ,14440   ,193.9,194.8,196.7
XS GIS Cut Line= 2
2191165.96169468626977.2473830182191786.93030243 626995.92313062
#Sta/Elev= 30
       0 2169.55    14.2 2164.61    50.2 2153.51    82.3 2147.37    98.3 2143.29
   114.3 2141.09   158.3 2128.15   166.3 2126.51   182.3 2124.68   198.3 2120.89
   230.3 2120.72     320 2123.34   350.4 2121.73   386.7 2121.45   394.3 2120.47
   401.32121.403   410.4 2124.02   426.4 2125.01   438.4 2127.28   462.4 2135.06
   490.4 2142.25   506.4  2145.7   522.4 2147.94   530.4  2150.5   550.5 2155.43
   562.5 2155.16   566.5 2155.67   574.5 2159.06   578.5 2160.11   621.2  2169.6
#Mann= 7 ,-1,0
       0      .1       0     230     .05       0     320      .1       0
   386.7    .045       0   401.3      .1       0     520     .05       0
     620     .06       0
Bank Sta=386.7,401.3
XS Rating Curve= 0 ,0
Exp/Cntr(USF)=0,0
Exp/Cntr=0.3,0.1

Type RM Length L Ch R = 1 ,14245   ,228.4,229.8,228.7
XS GIS Cut Line= 2
2191177.63403693627153.4997510082191779.92689708627161.670390584
#Sta/Elev= 30
       0 2154.87    14.5 2150.09    33.8 2148.67    58.5 2141.26    66.5 2137.99
    78.5 2135.61    94.5 2127.26   102.6 2119.62   106.6 2116.75   110.6 2114.87
   114.6 2114.19   122.6 2114.69   130.6 2116.88   162.6 2118.12   250.8 2119.27
   282.4 2118.78   288.22117.719   290.6 2117.03     2972117.714     310 2117.79
   345.6 2117.78   382.6 2122.02   390.6 2124.54   422.6  2130.8   467.9 2143.89
   482.6 2144.79   519.2 2158.72   550.6 2169.07   590.3 2180.33   602.3 2186.26
#Mann= 7 ,-1,0
       0      .1       0     210     .05       0   288.2    .045       0
     297     .05       0     310      .1       0     410     .05       0
     510     .06       0
Bank Sta=288.2,297
XS Rating Curve= 0 ,0
Exp/Cntr(USF)=0,0
Exp/Cntr=0.3,0.1

Type RM Length L Ch R = 1 ,14016   ,400.4,402.8,399.4
XS GIS Cut Line= 4
2191130.48517374627350.270195994 2191279.8868019627337.201960588
2191536.67151536627359.5712389032191750.54199119627375.322614644
#Sta/Elev= 30
       0 2171.15    37.8 2157.08      86 2141.18   134.2 2120.33   150.3 2111.14
   154.3 2110.01   174.4 2109.65   187.2 2111.68   279.5 2113.11   314.9 2112.21
     355 2112.66   379.2 2112.12   387.2 2111.42   391.2 2112.08   399.2 2114.39
   403.2 2117.44   407.2 2121.61   411.2 2123.48   439.3 2125.11   459.4 2127.15
   471.4 2130.01   483.4 2131.15   503.5 2134.93   522.4 2139.62   531.6 2143.31
   539.6 2145.03   552.7 2149.16   573.1 2156.72   607.8 2168.05   622.2 2173.65
#Mann= 4 ,-1,0
       0      .1       0  259.97     .05       0   379.2    .045       0
   391.2     .05       0
#XS Ineff= 1 ,-1
  297.09  341.712126.805
Permanent Ineff=
       F
Bank Sta=379.2,391.2
XS Rating Curve= 0 ,0
Exp/Cntr(USF)=0,0
Exp/Cntr=0.3,0.1

Type RM Length L Ch R = 1 ,13613   ,216,211,206.6
XS GIS Cut Line= 4
2191026.86391913 627544.782970282191238.79614884627561.933555343
 2191269.4221936627579.0841404062191646.73506499627628.085812015
#Sta/Elev= 30
       0 2164.56    25.4 2156.76    81.6 2141.19    93.6 2138.97   125.7 2130.31
   173.9 2118.47   189.9 2115.29     206 2109.95   214.2 2106.31     2252104.747
   244.62104.255     277 2103.99   294.8 2104.62     307 2105.86   401.5 2106.56
   407.8 2107.56   415.9 2112.49   423.9 2114.66   440.1 2115.61   468.3 2115.71
   476.4 2115.18   480.4 2115.66   492.5 2115.07   496.6 2116.72   500.6 2119.44
   503.4 2120.15   528.8 2123.54   589.3 2138.27   609.5 2143.95   628.2  2150.9
#Mann= 4 ,-1,0
       0      .1       0     225    .045       0   244.6      .1       0
  367.73     .05       0
#XS Ineff= 2 , 0
                          312.39         2113.11
Permanent Ineff=
       F       F
Bank Sta=225,244.6
XS Rating Curve= 0 ,0
Exp/Cntr(USF)=0,0
Exp/Cntr=0.3,0.1

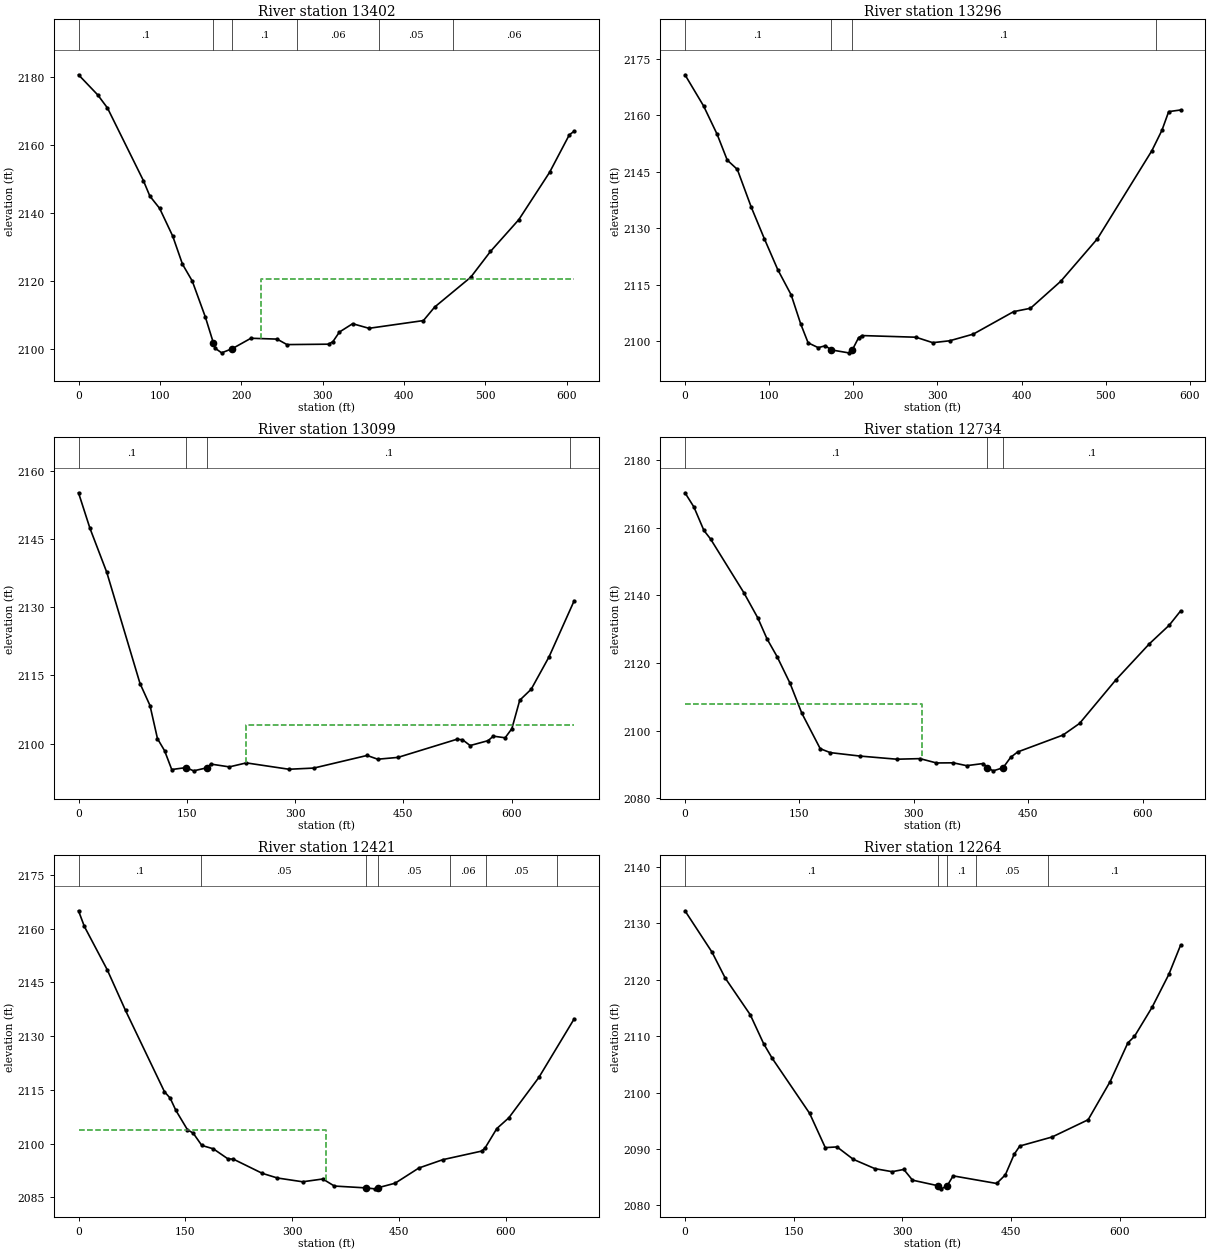
Type RM Length L Ch R = 1 ,13402   ,105.2,105.8,105.3
XS GIS Cut Line= 4
  2191028.643792627763.6544400192191256.98379839627777.719058285
2191456.90313748627803.7315807542191634.09150944627827.827763602
#Sta/Elev= 30
       0 2180.53    23.6 2174.63    35.6 2170.78    79.7 2149.49    87.7 2144.92
    99.7 2141.32   115.8 2133.17   127.8 2124.93   139.8    2120   155.9 2109.43
   165.82101.808   167.8 2100.29   175.9 2098.92   189.12100.157   211.9  2103.2
   244.1 2102.95   256.2 2101.34   307.3 2101.46   312.7 2102.22   320.7 2105.03
   336.9 2107.47     357 2106.12   423.9 2108.39   437.7 2112.35   482.1 2121.12
   506.3 2128.67   541.2 2138.02     579  2151.9   603.2 2162.89   609.2 2163.97
#Mann= 6 ,-1,0
       0      .1       0   165.8    .045       0   189.1      .1       0
  268.77     .06       0  368.77     .05       0  460.38     .06       0
#XS Ineff= 2 , 0
                          224.41         2120.53
Permanent Ineff=
       F       F
Bank Sta=165.8,189.1
XS Rating Curve= 0 ,0
Exp/Cntr(USF)=0,0
Exp/Cntr=0.3,0.1

Type RM Length L Ch R = 1 ,13296   ,190,197.4,205.8
XS GIS Cut Line= 2
2191034.06422724627870.181565221 2191622.3502767627897.027952398
#Sta/Elev= 30
       0 2170.75    22.1 2162.47    38.2 2154.94    50.2 2148.09    62.2 2145.61
    78.8 2135.55    94.2 2127.25   110.2    2119   126.2 2112.26   137.5 2104.56
   146.3 2099.54   158.3 2098.26   166.9 2098.77   173.4 2097.68   194.3 2096.88
   198.82097.649   206.3 2100.92   210.3 2101.47   274.4 2101.03   294.4 2099.58
   314.4 2100.08   342.5 2101.85   390.5 2107.83   410.5 2108.72   446.6 2115.92
     490 2127.18   554.7 2150.57   566.7 2156.01   574.7 2160.96   588.9  2161.4
#Mann= 4 ,-1,0
       0      .1       0   173.4    .045       0   198.8      .1       0
     560     .06       0
Bank Sta=173.4,198.8
XS Rating Curve= 0 ,0
Exp/Cntr(USF)=0,0
Exp/Cntr=0.3,0.1

Type RM Length L Ch R = 1 ,13099   ,348.3,364.5,354.8
XS GIS Cut Line= 3
2191035.23146147627963.5603032292191475.27876433628278.713544007
2191592.00218684628192.338211349
#Sta/Elev= 30
       0 2155.24    15.9 2147.39    39.1 2137.74    85.2 2113.22      99 2108.38
   109.4 2101.06   119.2 2098.43   129.1 2094.28   148.8  2094.7   159.5 2093.99
   178.3 2094.68   183.2 2095.48   208.9 2094.86   232.4 2095.74   291.4 2094.34
   325.9  2094.6   399.7 2097.38   414.4 2096.55   442.4 2096.95   523.6 2100.92
   531.8 2100.85   542.4 2099.56   567.3 2100.64   574.5 2101.63   590.9 2101.27
   600.2 2103.28   611.1 2109.54     627 2111.97   651.7  2119.1   686.5 2131.45
#Mann= 4 ,-1,0
       0      .1       0   148.8    .045       0   178.3      .1       0
  681.26     .06       0
#XS Ineff= 2 , 0
                          232.06         2104.04
Permanent Ineff=
       F       F
Bank Sta=148.8,178.3
XS Rating Curve= 0 ,0
Exp/Cntr(USF)=0,0
Exp/Cntr=0.3,0.1

Type RM Length L Ch R = 1 ,12734   ,303.1,312.8,311.2
XS GIS Cut Line= 2
2190925.51144431627990.4066904072191183.47020806628586.863379434
#Sta/Elev= 30
       0 2170.36    11.7 2166.16    24.8 2159.23    33.5 2156.71    77.1 2140.85
    95.4 2133.39   107.6 2127.15   120.7 2121.94   137.7 2114.05   153.2 2105.18
   177.3  2094.7   190.4 2093.54   229.3 2092.52   277.6 2091.59   308.1 2091.76
   329.7 2090.48   351.7 2090.52   369.2 2089.68   390.9 2090.31   396.6  2089.1
     404 2088.15     417 2089.06     427 2092.15   436.1 2093.73   495.5 2098.72
   517.3 2102.17   565.2 2115.13   608.8 2125.71   634.9 2131.22   649.8 2135.44
#Mann= 3 ,-1,0
       0      .1       0   396.6    .045       0     417      .1       0
#XS Ineff= 2 , 0
          311.11 2107.97
Permanent Ineff=
       F       F
Bank Sta=396.6,417
XS Rating Curve= 0 ,0
Exp/Cntr(USF)=0,0
Exp/Cntr=0.3,0.1

Type RM Length L Ch R = 1 ,12421   ,155.6,157.3,158.7
BEGIN DESCRIPTION:
Structure
END DESCRIPTION:
XS GIS Cut Line= 4
2190839.74272328628000.991403804 2190826.9031468628142.226745041
2190871.25804735628438.7042382172190950.62997466628680.321722813
#Sta/Elev= 30
       0 2164.99     8.2 2160.62    40.3 2148.53      66 2137.16   120.7 2114.46
   128.7 2112.68   136.7 2109.26   152.9 2103.88     161 2102.91   173.1 2099.48
   189.3 2098.53   209.5 2095.77   217.6 2095.63     258 2091.69   279.2 2090.39
   314.7 2089.33     343 2090.11   359.2 2088.14   403.7 2087.62   415.8 2087.36
     420 2087.64   444.5 2088.93   477.9 2093.18   511.6 2095.51   566.3 2097.91
   571.1 2098.86   587.3 2104.19   604.2  2107.2   646.3 2118.45   695.9 2134.81
#Mann= 7 ,-1,0
       0      .1       0  171.82     .05       0   403.7    .045       0
     420     .05       0  521.59     .06       0  571.59     .05       0
  671.59     .06       0
#XS Ineff= 2 , 0
          346.81 2103.75
Permanent Ineff=
       F       F
Bank Sta=403.7,420
XS Rating Curve= 0 ,0
Exp/Cntr(USF)=0,0
Exp/Cntr=0.3,0.1

Type RM Length L Ch R = 1 ,12264   ,269,273.5,273.7
XS GIS Cut Line= 4
2190646.54246451628077.9492572892190720.07822069628255.368859505
2190704.90417577628514.4948574772190797.11567955628728.098720671
#Sta/Elev= 30
       0 2132.24    37.4 2124.89    55.5 2120.32    90.1 2113.81   108.7 2108.65
   120.4 2106.09   172.1 2096.32   193.7 2090.25   209.9 2090.37   232.4 2088.17
   262.2 2086.52     286 2085.98   302.1 2086.38   314.1 2084.48   348.9  2083.5
   354.1 2082.94   362.2 2083.53   370.2 2085.24   430.3 2083.89   442.3 2085.42
   454.5 2089.06   462.2 2090.53   506.8 2092.13   556.6 2095.19     587 2101.96
   611.4 2108.81   620.5 2109.96   644.8 2115.11     668 2120.96   684.3 2126.16
#Mann= 5 ,-1,0
       0      .1       0   348.9    .045       0   362.2      .1       0
  402.06     .05       0  501.63      .1       0
Bank Sta=348.9,362.2
XS Rating Curve= 0 ,0
Exp/Cntr(USF)=0,0
Exp/Cntr=0.3,0.1