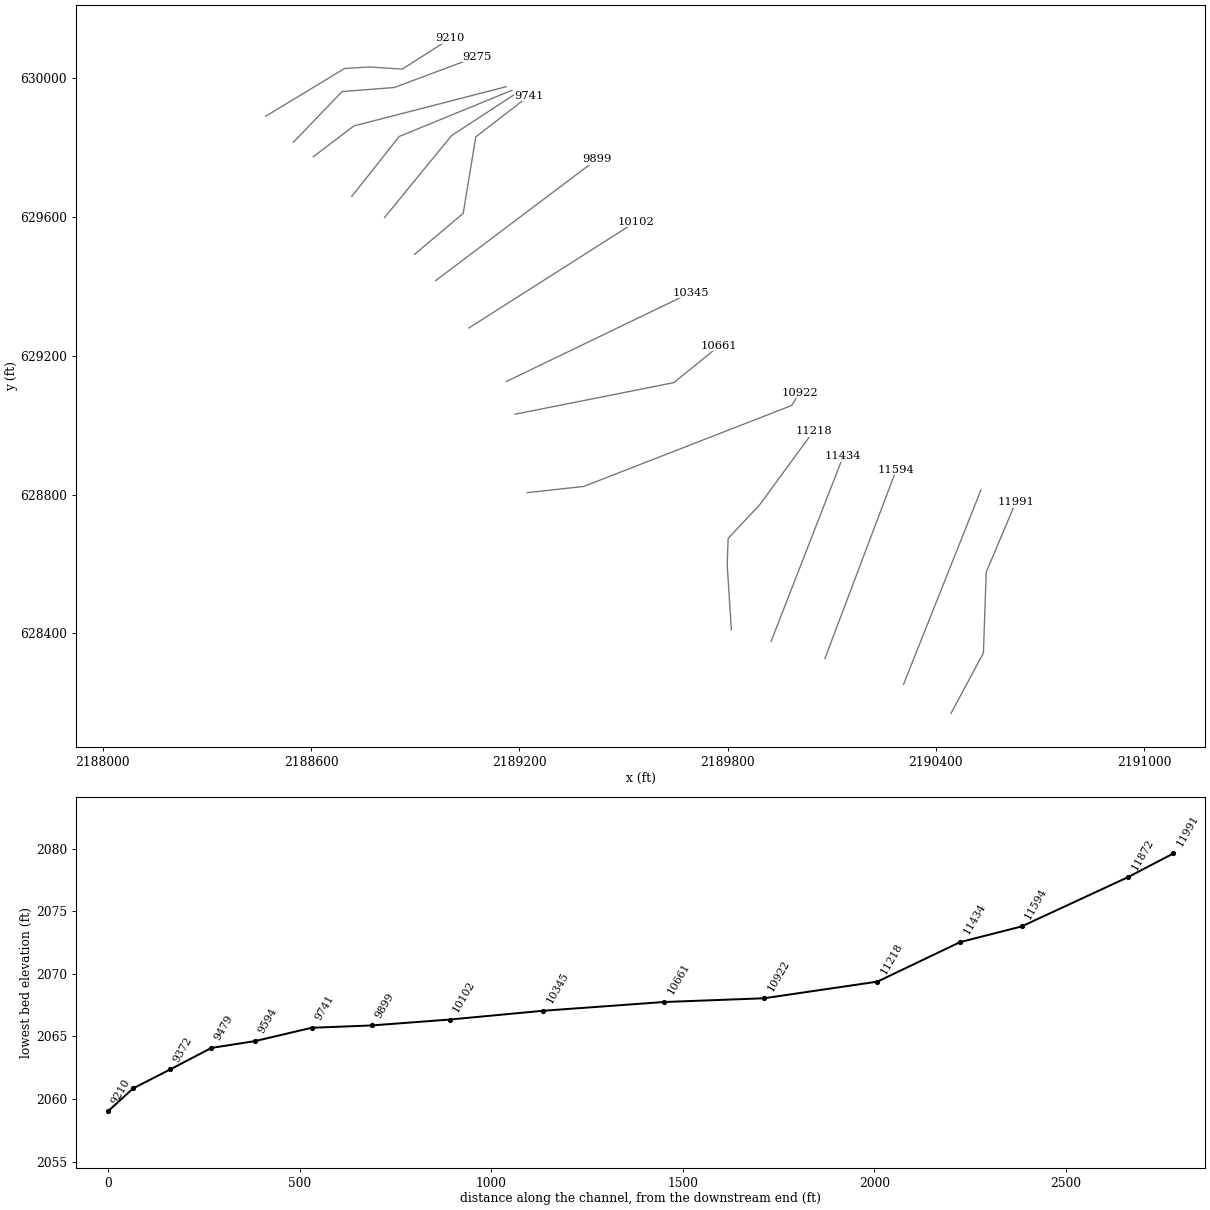
HEC-RAS study MFRFBUCKRV.prj: MFRFBUCKRV

--- MFRFBUCKRV.g01 (geometry) --- (continued)

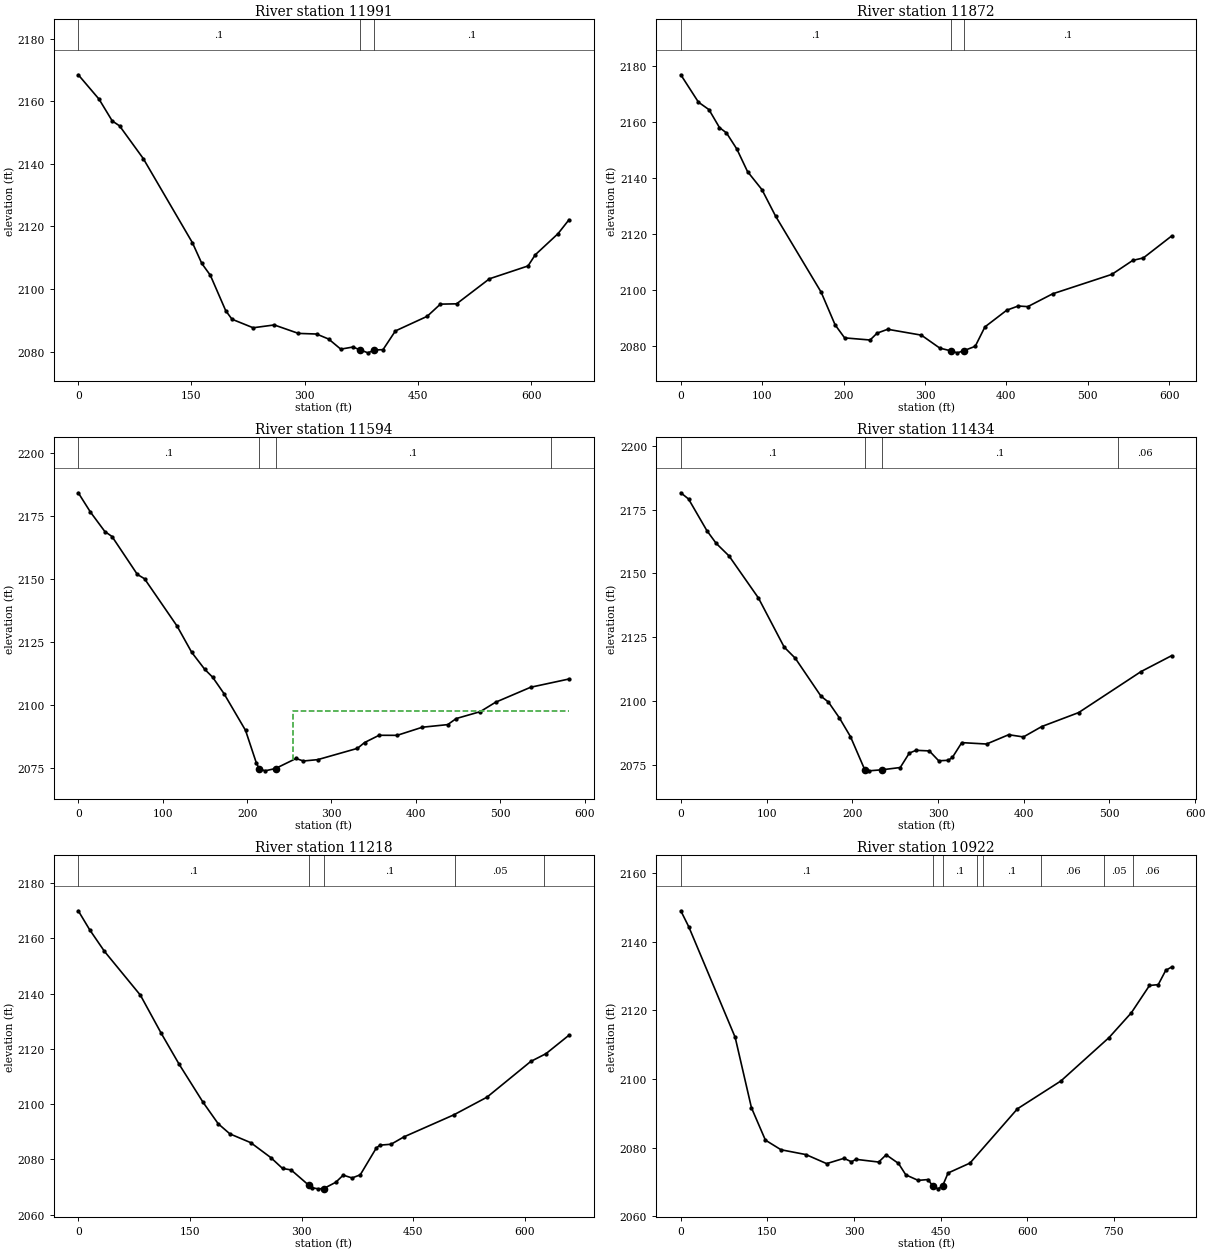
Type RM Length L Ch R = 1 ,11991   ,122.5,118.7,115.7
XS GIS Cut Line= 4
2190443.44370934628168.9935268472190536.82244735628342.911426387
2190544.99308693628576.3582714082190630.20118536628778.289792351
#Sta/Elev= 30
       0 2168.47    27.5 2160.69      45 2153.73    54.7 2152.15    86.1 2141.71
   151.3 2114.79   163.7 2108.18     175 2104.41   195.4 2093.08   203.7 2090.37
   231.7 2087.64   259.7 2088.54   291.7 2085.84   315.7 2085.64   331.8 2084.03
   347.8 2080.81   363.8 2081.48     373 2080.63   383.8 2079.63   392.3 2080.53
   403.8 2080.65   420.2 2086.63   462.3  2091.3   479.8 2095.19   501.3 2095.29
   544.8 2103.29   595.9 2107.39   605.5 2110.95   635.6 2117.69   650.2 2122.15
#Mann= 3 ,-1,0
       0      .1       0     373    .045       0   392.3      .1       0
Bank Sta=373,392.3
XS Rating Curve= 0 ,0
Exp/Cntr(USF)=0,0
Exp/Cntr=0.3,0.1

Type RM Length L Ch R = 1 ,11872   ,279.5,277.8,278.1
XS GIS Cut Line= 2
2190306.87730501628253.034391055  2190529.819042628813.306819104
#Sta/Elev= 30
       0 2177.01    21.7 2167.22    34.6 2164.57    47.5 2158.17    56.1 2156.26
    68.9 2150.48      82 2142.44    99.7 2136.01   116.4 2126.58   172.4 2099.42
   189.6 2087.73   201.3 2083.07   232.6 2082.31   241.2 2084.76   254.2 2086.14
   295.6 2084.05   318.3 2079.41   331.6 2078.46   339.9 2077.73   348.3 2078.56
   361.8 2080.06   373.7 2086.99   400.5 2092.95   414.6 2094.45   426.4 2094.23
   456.9  2098.8   529.7 2105.75   555.4 2110.74   568.4 2111.62     603 2119.42
#Mann= 3 ,-1,0
       0      .1       0   331.6    .045       0   348.3      .1       0
Bank Sta=331.6,348.3
XS Rating Curve= 0 ,0
Exp/Cntr(USF)=0,0
Exp/Cntr=0.3,0.1

Type RM Length L Ch R = 1 ,11594   ,160.6,160.4,160.4
XS GIS Cut Line= 2
2190080.43386534628327.7373814612190285.86708895628871.668530359
#Sta/Elev= 30
       0 2184.06    14.4 2176.42    31.5 2168.69      40 2166.72      70 2151.68
    78.5 2149.97     117 2131.23   134.4 2120.79   149.9 2114.02   159.2 2110.93
   172.6 2104.44   198.2 2089.82   211.1  2076.8   214.4 2074.68   221.3 2073.79
   233.7 2074.71   258.1  2078.7   266.6 2077.69   283.7 2078.23   330.8 2082.71
   339.2 2085.01   356.4 2087.89   377.8 2087.87   407.7 2091.09   437.7 2092.12
   447.8 2094.53   476.2 2097.25   494.4 2100.99     536 2106.94   581.4 2110.21
#Mann= 4 ,-1,0
       0      .1       0   214.4    .045       0   233.7      .1       0
     560     .06       0
#XS Ineff= 2 , 0
                          254.64         2097.68
Permanent Ineff=
       F       F
Bank Sta=214.4,233.7
XS Rating Curve= 0 ,0
Exp/Cntr(USF)=0,0
Exp/Cntr=0.3,0.1

Type RM Length L Ch R = 1 ,11434   ,219.6,215.8,212.1
XS GIS Cut Line= 2
 2189925.1917134628376.7612189162190132.95940547628910.187259787
#Sta/Elev= 30
       0 2181.64       9 2179.21    30.5 2166.74    41.3 2161.79    56.3 2156.85
    90.6 2140.34   120.6 2121.09   133.5 2116.74   163.6 2101.81   172.2 2099.54
     185 2093.32   197.9 2085.98   214.62072.993   219.4 2072.54   234.6 2072.95
     256 2073.84   266.6 2079.51   274.5 2080.59   289.9 2080.36   300.9 2076.48
   311.9 2076.68   316.8 2077.78   327.8 2083.61   356.7 2083.06   382.5 2086.71
   399.7 2085.84   421.1 2089.92   464.1 2095.39     537  2111.5   572.5 2117.71
#Mann= 4 ,-1,0
       0      .1       0   214.6    .045       0   234.6      .1       0
     510     .06       0
Bank Sta=214.6,234.6
XS Rating Curve= 0 ,0
Exp/Cntr(USF)=0,0
Exp/Cntr=0.3,0.1

Type RM Length L Ch R = 1 ,11218   ,298.5,296.2,290.7
XS GIS Cut Line= 5
2189810.62105599628409.8787362782189798.64258555628597.528160612
2189801.40176757628673.7498526742189891.81524294628769.902148663
 2190047.0234379628982.098792485
#Sta/Elev= 30
       0 2170.02    15.3 2163.16    35.2 2155.33    83.5 2139.46   111.5 2125.65
   135.6 2114.43   167.6 2100.72     188 2092.93   203.7 2089.27   231.7 2086.09
   258.7 2080.68   274.4 2076.76   285.9 2076.23     3102070.602     314 2069.76
   322.5 2069.38   329.82069.499   345.9 2071.75   355.9 2074.34   367.8 2073.32
   378.8 2074.45   400.3 2084.14   405.3 2085.19   420.2 2085.52   437.5 2088.19
   504.4 2096.15     549 2102.55   607.8 2115.48   628.3  2118.3   659.2 2124.99
#Mann= 5 ,-1,0
       0      .1       0     310    .045       0   329.8      .1       0
  506.29     .05       0  626.29     .06       0
Bank Sta=310,329.8
XS Rating Curve= 0 ,0
Exp/Cntr(USF)=0,0
Exp/Cntr=0.3,0.1

Type RM Length L Ch R = 1 ,10922   ,260.3,261.2,256.7
BEGIN DESCRIPTION:
Structure
END DESCRIPTION:
XS GIS Cut Line= 4
 2189222.4945417628805.4437557292189385.38856245628823.341347181
  2189984.568798629056.7881922012190007.39471174629093.620916637
#Sta/Elev= 30
       0    2149    13.8 2144.34    94.2 2112.16   122.4 2091.66   146.6 2082.23
   173.6 2079.43   216.9 2078.02   252.7 2075.39   282.8 2076.94   295.7 2075.92
   303.4 2076.64   342.9 2075.85   355.8 2077.96   377.2 2075.45   389.9 2072.12
   411.3 2070.51   428.7 2070.76   436.2 2068.91   445.9 2068.05   453.9 2069.01
   463.1 2072.66   501.1 2075.55   583.3 2091.35   658.6 2099.45   742.1  2112.1
   780.7 2119.31   812.1 2127.25   827.3  2127.5   840.3 2131.67   850.3 2132.61
#Mann= 8 ,-1,0
       0      .1       0   436.2    .045       0   453.9      .1       0
  513.87     .05       0  523.87      .1       0  623.87     .06       0
  733.87     .05       0  783.87     .06       0
Bank Sta=436.2,453.9
XS Rating Curve= 0 ,0
Exp/Cntr(USF)=0,0
Exp/Cntr=0.3,0.1

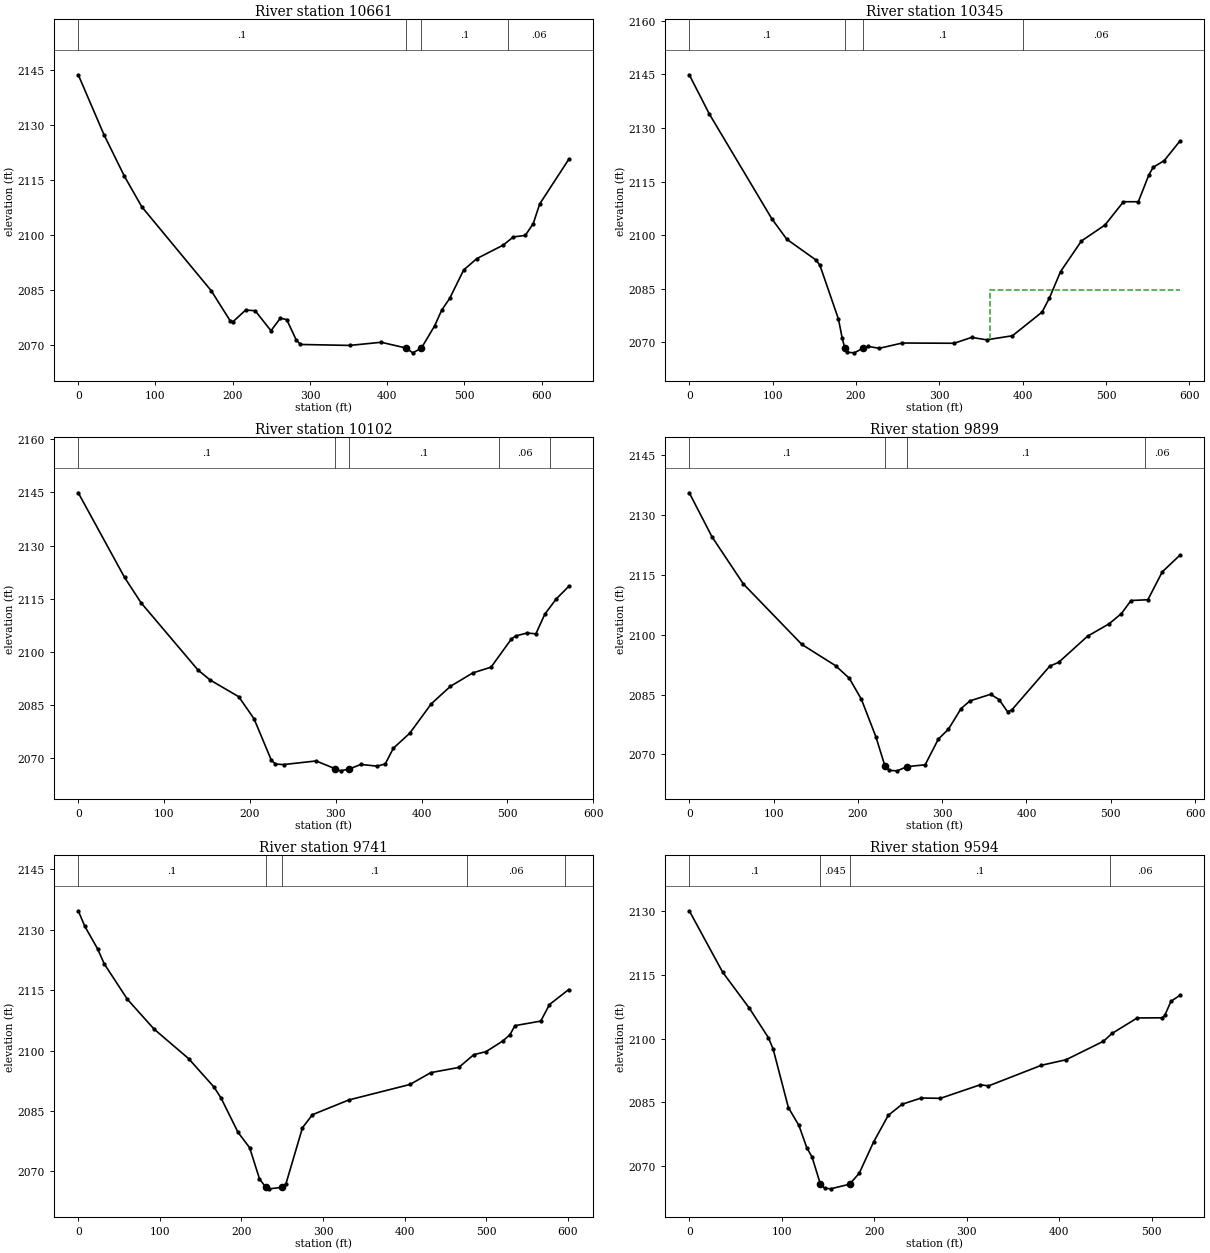
Type RM Length L Ch R = 1 ,10661   ,310.7,315.7,313.9
XS GIS Cut Line= 3
2189187.49968313629031.5796191982189645.05549937629122.623888756
2189775.78573258 629228.84220324
#Sta/Elev= 30
       0 2143.81    33.3 2127.42    59.8 2116.04    82.3 2107.69   172.2 2084.73
   196.5 2076.58   200.5 2076.29   216.8 2079.47   229.1 2079.26   249.5  2073.8
   261.7 2077.24   269.9 2076.84   282.1 2071.32   287.7 2070.04   351.4 2069.78
   392.2 2070.64   424.8 2069.05     433 2067.75   444.1    2069   461.5 2075.17
   470.5 2079.41   480.9 2082.65     499 2090.42   516.1 2093.54   550.2 2097.22
   563.3 2099.45   578.8 2099.88   589.1 2103.12   597.4 2108.47     635 2120.67
#Mann= 4 ,-1,0
       0      .1       0   424.8    .045       0   444.1      .1       0
  556.53     .06       0
Bank Sta=424.8,444.1
XS Rating Curve= 0 ,0
Exp/Cntr(USF)=0,0
Exp/Cntr=0.3,0.1

Type RM Length L Ch R = 1 ,10345   ,242.7,243.3,242.5
XS GIS Cut Line= 2
2189162.98776441629126.125591431 2189692.9121026629381.749886728
#Sta/Elev= 30
       0 2144.89    24.1  2133.9      99 2104.59     117 2098.85   152.3 2092.99
   156.8 2091.51     179 2076.48   183.4 2071.23   186.62068.337   188.9 2067.23
   197.9 2067.05   208.12068.288   214.5 2068.84     228 2068.32   255.6  2069.8
   317.7 2069.73   338.7 2071.37   356.7  2070.7   387.7 2071.83   423.2 2078.45
   432.1 2082.43   445.4 2089.79   470.5 2098.37   498.7 2102.83   520.9 2109.35
   538.7 2109.35   551.4 2116.89   556.5 2118.99   569.8 2120.87   588.4 2126.28
#Mann= 4 ,-1,0
       0      .1       0   186.6    .045       0   208.1      .1       0
     400     .06       0
#XS Ineff= 2 , 0
                          360.66         2084.54
Permanent Ineff=
       F       F
Bank Sta=186.6,208.1
XS Rating Curve= 0 ,0
Exp/Cntr(USF)=0,0
Exp/Cntr=0.3,0.1

Type RM Length L Ch R = 1 ,10102   ,203.6,202.6,202.1
XS GIS Cut Line= 2
2189054.43498147629280.2005091442189536.50271644629587.183110346
#Sta/Elev= 30
       0  2144.9    53.9 2121.01    73.2 2113.82   139.6 2094.81   153.8 2091.99
     187 2087.29   204.8 2081.07   224.9  2069.4   229.7 2068.26   239.2 2068.12
   277.1 2069.14   299.7 2066.91   305.6 2066.35   315.8 2066.88   329.4 2068.16
   348.2 2067.67   357.7  2068.3   367.2 2072.75   386.2 2076.96   411.4  2085.3
   433.7 2090.23   459.7 2094.01     481 2095.64   504.7  2103.6   509.5 2104.44
   523.1  2105.3   533.2 2105.04   543.7 2110.62   556.9  2114.9   571.5 2118.46
#Mann= 5 ,-1,0
       0      .1       0   299.7    .045       0   315.8      .1       0
     490     .06       0     550      .1       0
Bank Sta=299.7,315.8
XS Rating Curve= 0 ,0
Exp/Cntr(USF)=0,0
Exp/Cntr=0.3,0.1

Type RM Length L Ch R = 1 ,9899    ,149.3,158.1,165.3
XS GIS Cut Line= 2
2188958.72177501629416.766913481 2189423.2809966629766.937181012
#Sta/Elev= 30
       0 2135.57    26.9 2124.56    64.2 2112.71   133.6 2097.55   173.5 2092.24
   189.8 2089.09   204.1 2083.85   221.3 2074.45   232.2 2067.02   237.2 2065.99
   246.6 2065.88   258.4 2066.94   279.8 2067.39   295.5 2073.85   307.4  2076.3
   322.4 2081.49     333 2083.42   357.5 2085.07   367.5 2083.74   377.5  2080.7
   382.5 2081.12   427.6 2092.12   438.3 2093.09   472.5 2099.64   497.7 2102.68
   512.6 2105.29     524 2108.57     544 2108.76   561.1 2115.76   581.8 2119.89
#Mann= 4 ,-1,0
       0      .1       0   232.2    .045       0   258.4      .1       0
     540     .06       0
Bank Sta=232.2,258.4
XS Rating Curve= 0 ,0
Exp/Cntr(USF)=0,0
Exp/Cntr=0.3,0.1

Type RM Length L Ch R = 1 ,9741    ,155.1,146.9,141.2
XS GIS Cut Line= 4
2188898.02559531629492.6371381132189038.09370232629610.527794848
 2189074.2779633629831.1350633922189228.35288101629950.192954353
#Sta/Elev= 30
       0 2134.73       8 2130.89    23.7 2125.29    31.9 2121.54    60.3 2112.74
    92.8 2105.38   135.3 2098.02   166.6 2090.92   175.1 2088.22   195.9 2079.71
   210.1 2075.91   222.2 2068.16     2302066.043   234.4 2065.69   249.82066.069
   254.7    2067   274.9 2080.87   287.1  2084.1   331.7 2087.76   406.6  2091.6
   432.3 2094.55   466.5 2095.83   484.9    2099     500 2099.76   520.7 2102.43
   529.2 2103.96   535.4 2106.21     567 2107.34   577.7 2111.45   601.3 2115.18
#Mann= 5 ,-1,0
       0      .1       0     230    .045       0   249.8      .1       0
  476.63     .06       0  596.63      .1       0
Bank Sta=230,249.8
XS Rating Curve= 0 ,0
Exp/Cntr(USF)=0,0
Exp/Cntr=0.3,0.1

Type RM Length L Ch R = 1 ,9594    ,114.1,114.6,114.9
XS GIS Cut Line= 3
2188811.65026265629598.8554525972189004.24390979629834.636766068
2189193.33585426629958.363593929
#Sta/Elev= 30
       0 2130.16    36.1 2115.69      65 2107.19    85.6 2100.25    90.8 2097.49
   107.2 2083.77   118.6 2079.56   127.1 2074.32   132.8 2072.11   141.82065.744
   146.3 2064.79   152.8 2064.63   173.4 2065.72   183.8 2068.31   199.3 2075.66
   215.2 2081.95   230.3 2084.58   250.9 2086.04   271.6 2085.96   314.9 2089.17
   323.5 2088.88   380.8 2093.75   407.4 2095.05   447.8  2099.4   457.3 2101.27
   484.4  2104.9   511.4 2104.94   514.3 2105.53   520.9 2108.83   530.4  2110.2
#Mann= 4 ,-1,0
       0      .1       0   141.8    .045       0   173.4      .1       0
  454.44     .06       0
Bank Sta=141.8,173.4
XS Rating Curve= 0 ,0
Exp/Cntr(USF)=0,0
Exp/Cntr=0.3,0.1

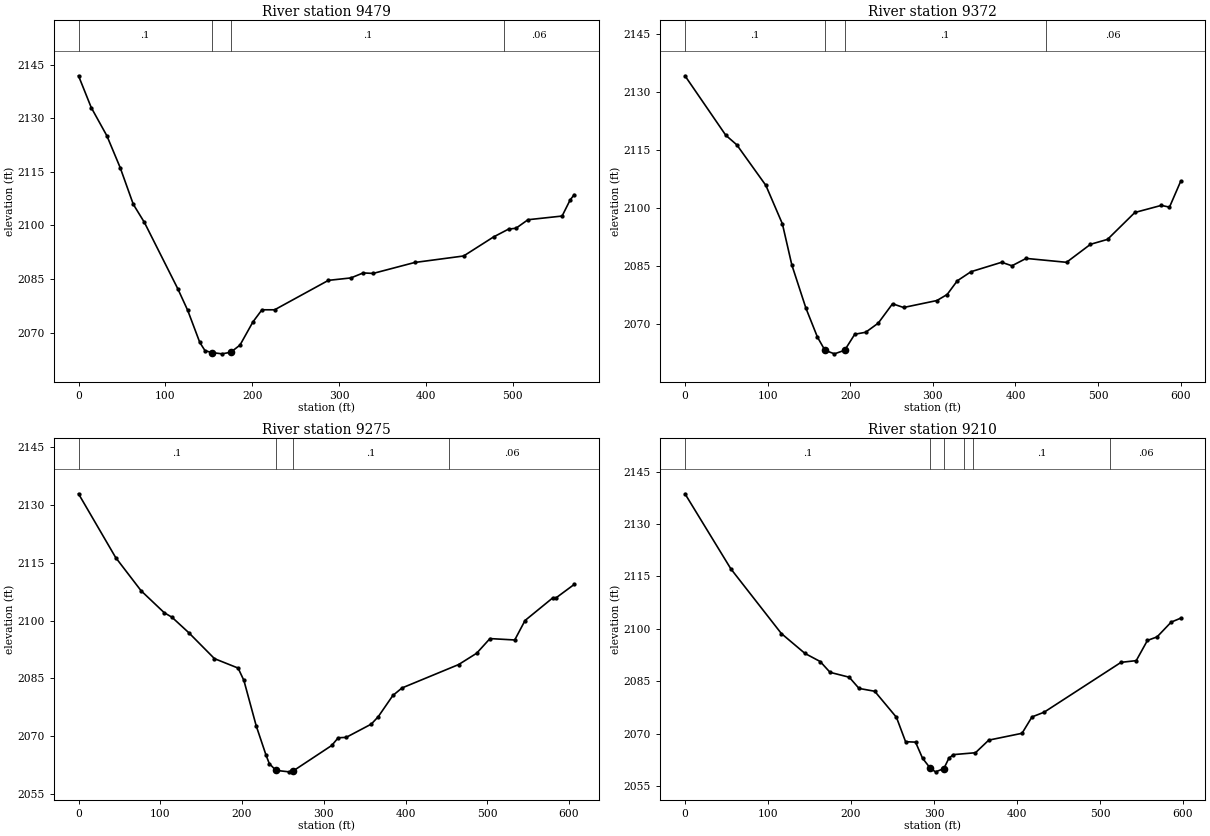
Type RM Length L Ch R = 1 ,9479    ,113.8,107.6,98.7
XS GIS Cut Line= 3
2188717.10429042629659.5516323022188853.67069475629832.302297618
2189178.16180933629965.366999279
#Sta/Elev= 30
       0 2141.85    14.7 2132.94    32.7 2125.05      48 2116.16    63.1  2105.9
    75.9 2100.83   114.3 2082.31   125.8 2076.23   139.7 2067.26   145.7 2064.97
   153.3 2064.45   165.2 2064.08   175.32064.516     186 2066.53   200.9 2073.01
   211.3  2076.4   225.9  2076.4   287.8 2084.63   313.7 2085.31   327.9 2086.71
   339.3 2086.57   387.2 2089.63   443.6 2091.45     478 2096.77   495.3 2098.96
   503.9 2099.21   517.7 2101.59     557 2102.62   566.2 2107.09   570.9 2108.59
#Mann= 4 ,-1,0
       0      .1       0   153.3    .045       0   175.3      .1       0
  490.21     .06       0
Bank Sta=153.3,175.3
XS Rating Curve= 0 ,0
Exp/Cntr(USF)=0,0
Exp/Cntr=0.3,0.1

Type RM Length L Ch R = 1 ,9372    ,98.5,96.8,94.6
XS GIS Cut Line= 3
2188606.21703903629773.9405863632188722.94046154 629862.65038747
2189161.82053018629975.872107305
#Sta/Elev= 30
       0  2134.3    49.4 2118.91    62.7 2116.44    97.9 2105.94   117.9 2095.99
   129.3 2085.38   146.4 2074.16   160.3  2066.7   169.4 2063.28   180.9 2062.36
   193.3 2063.29   205.5 2067.43   218.7 2067.94   233.9  2070.3   251.2 2075.31
   264.6 2074.35   304.9 2076.15   317.3 2077.71   329.6 2081.26   346.2 2083.61
   383.3 2086.05   395.7 2085.14   412.9 2087.05   461.8 2086.04   490.8  2090.7
   511.4 2091.97   544.5 2098.93   576.6 2100.77   586.4 2100.31   599.9 2106.97
#Mann= 4 ,-1,0
       0      .1       0   169.4    .045       0   193.3      .1       0
  436.61     .06       0
Bank Sta=169.4,193.3
XS Rating Curve= 0 ,0
Exp/Cntr(USF)=0,0
Exp/Cntr=0.3,0.1

Type RM Length L Ch R = 1 ,9275    ,65.5,65.4,65.3
XS GIS Cut Line= 4
  2188549.022562629815.9610184662188689.09066901629961.865296604
2188839.66388405629973.5376388552189076.61243175630062.247439963
#Sta/Elev= 30
       0 2132.81    45.5 2116.29    76.6  2107.7   104.9 2102.02   114.3 2100.86
   134.8 2096.87   166.3 2090.14   195.2  2087.7   202.3  2084.5   217.4 2072.72
   229.4 2065.15   233.4 2062.96   241.5 2061.22   257.5 2060.84   262.82061.104
   309.7 2067.66   317.7 2069.66   327.4 2069.76   358.1 2073.19   366.6  2075.1
   384.5  2080.6   395.7 2082.55   464.9  2088.6     487 2091.53   503.3 2095.33
   533.6 2094.97   546.2 2100.01   580.2 2105.88   584.5 2105.93   606.3 2109.34
#Mann= 4 ,-1,0
       0      .1       0   241.5    .045       0   262.8      .1       0
  453.28     .06       0
Bank Sta=241.5,262.8
XS Rating Curve= 0 ,0
Exp/Cntr(USF)=0,0
Exp/Cntr=0.3,0.1

Type RM Length L Ch R = 1 ,9210    ,320.4,325.9,330.7
XS GIS Cut Line= 5
2188468.86060696629890.5556420562188696.08100183630028.323062007
2188767.80226128630032.6988321352188862.67192195630026.570237682
 2189001.2491063630115.313076734
#Sta/Elev= 30
       0 2138.66    55.3 2117.15   116.1 2098.64   144.6 2092.93   162.9 2090.62
   174.8 2087.52   197.9 2086.12   209.7 2082.91   228.6  2082.1   254.8 2074.63
   265.8 2067.65   277.8 2067.53   286.2 2062.93   295.8 2059.99   301.9 2059.02
   311.9 2059.94   311.9 2059.95   317.9 2062.89   323.3 2063.95     350 2064.49
     366  2068.1   406.1 2070.06   418.1 2074.75   432.7  2076.1   525.4 2090.38
   543.7 2090.87   557.2 2096.66   568.8 2097.67   585.8  2101.9   597.2 2103.02
#Mann= 6 ,-1,0
       0      .1       0   295.8    .045       0   311.9      .1       0
  335.72     .05       0  347.58      .1       0  512.65     .06       0
Bank Sta=295.8,311.9
XS Rating Curve= 0 ,0
Exp/Cntr(USF)=0,0
Exp/Cntr=0.3,0.1