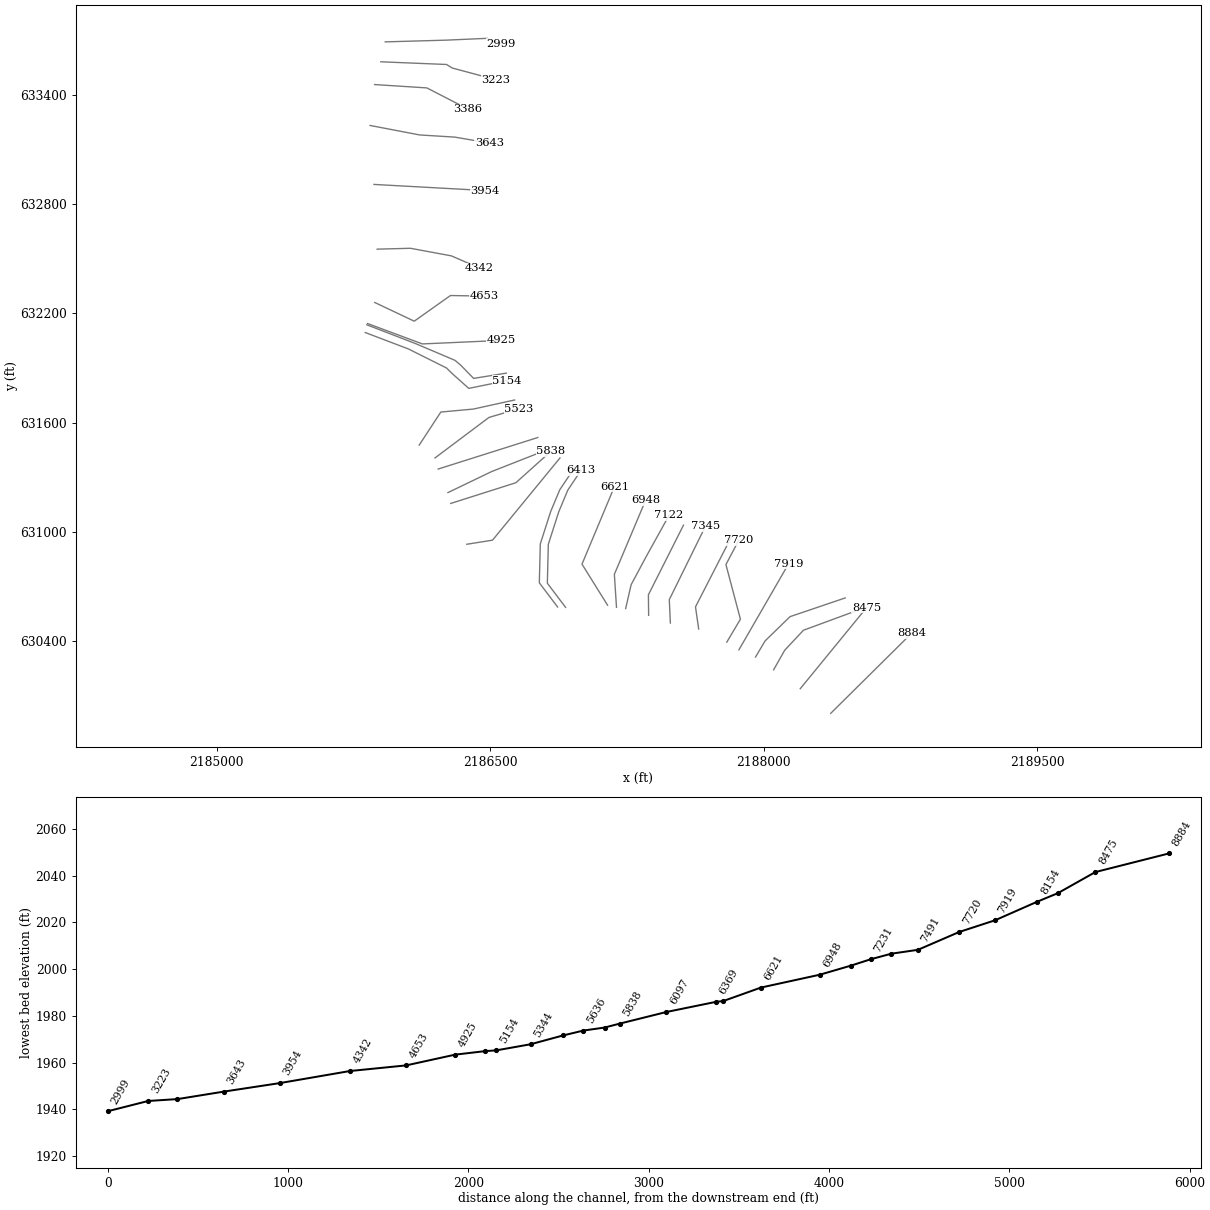
HEC-RAS study MFRFBUCKRV.prj: MFRFBUCKRV

--- MFRFBUCKRV.g01 (geometry) --- (continued)

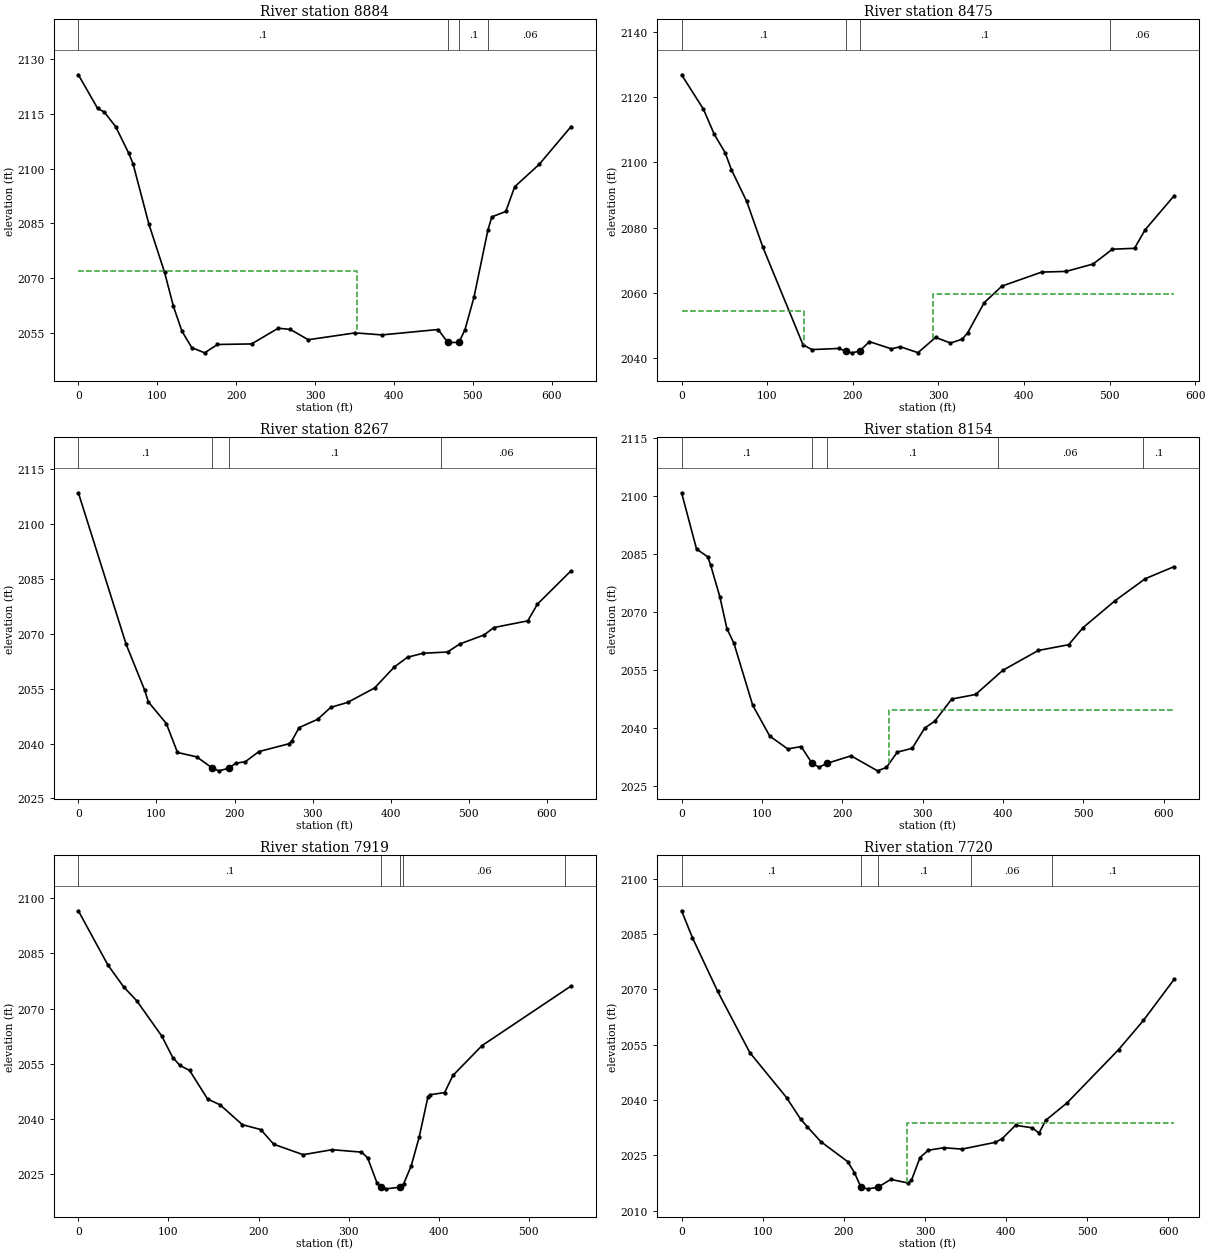
Type RM Length L Ch R = 1 ,8884    ,408.3,408.8,408.4
XS GIS Cut Line= 2
2188366.93402289630003.8857287082188810.48302843630443.933031571
#Sta/Elev= 30
       0 2125.71    24.4  2116.5    32.9  2115.5    47.3  2111.5      64 2104.16
    69.4 2101.29    89.5 2084.75   109.3 2071.61   120.6 2062.25   131.3 2055.51
   143.8 2050.97   160.2 2049.55   176.4 2051.84   219.6 2051.99   253.5  2056.3
   268.8 2055.96   291.5 2053.14   351.1 2055.02   384.9 2054.46   456.2 2055.94
   468.5 2052.39   482.6  2052.4   490.3 2055.91   501.6 2064.71   519.4 2083.26
   524.3 2086.79     542 2088.27   553.3 2095.04   584.5  2101.2   624.8 2111.53
#Mann= 4 ,-1,0
       0      .1       0   468.5    .045       0   482.6      .1       0
     520     .06       0
#XS Ineff= 2 , 0
          353.19 2071.93
Permanent Ineff=
       F       F
Bank Sta=468.5,482.6
XS Rating Curve= 0 ,0
Exp/Cntr(USF)=0,0
Exp/Cntr=0.3,0.1

Type RM Length L Ch R = 1 ,8475    ,207.8,207.8,205
XS GIS Cut Line= 2
 2188200.0195287 630139.284898822188564.19660693630585.168372809
#Sta/Elev= 30
       0 2126.84    25.5  2116.3    38.2 2108.58    50.8 2102.98    58.3 2097.67
    76.1    2088    95.1 2073.87   141.9 2044.02   152.2 2042.56   183.6  2042.9
   191.9 2042.09   198.7 2041.56   207.92042.064   219.4    2045   245.2 2042.78
   255.5 2043.44   276.2 2041.61   296.8 2046.29   314.2 2044.57   327.8 2045.74
   334.1 2047.63   353.6 2056.96   374.3 2062.03   420.8 2066.33   449.2 2066.53
   480.8  2068.8   503.4 2073.34   529.2 2073.62   541.6 2079.29   575.7 2089.81
#Mann= 4 ,-1,0
       0      .1       0   191.9    .045       0   207.9      .1       0
     500     .06       0
#XS Ineff= 2 , 0
          143.17 2054.25  293.99         2059.53
Permanent Ineff=
       F       F
Bank Sta=191.9,207.9
XS Rating Curve= 0 ,0
Exp/Cntr(USF)=0,0
Exp/Cntr=0.3,0.1

Type RM Length L Ch R = 1 ,8267    ,113.8,113.3,113.5
XS GIS Cut Line= 4
2188054.11525056630243.1687448542188114.81143026630350.554293563
2188217.52804207630460.2743107232188552.52426468630584.001138584
#Sta/Elev= 30
       0 2108.52    61.1 2067.15      85 2054.51    89.6 2051.37   112.6 2045.46
   126.9 2037.55   151.6 2036.34   171.5 2033.28   179.9 2032.53   192.7 2033.25
   201.4 2034.59   213.9 2035.04   231.1 2037.79   269.4 2039.92   273.3 2040.74
   282.6 2044.34   306.3 2046.61   323.1 2049.87   344.9 2051.25   379.2 2055.17
   404.4  2060.9   421.4 2063.58   441.5 2064.67   472.6    2065   488.2 2067.19
   519.5 2069.67   531.8 2071.69   575.4 2073.52   587.7 2078.09   630.8 2087.21
#Mann= 4 ,-1,0
       0      .1       0   171.5    .045       0   192.7      .1       0
  463.65     .06       0
Bank Sta=171.5,192.7
XS Rating Curve= 0 ,0
Exp/Cntr(USF)=0,0
Exp/Cntr=0.3,0.1

Type RM Length L Ch R = 1 ,8154    ,227.8,234.8,235.4
XS GIS Cut Line= 4
2187954.90034143 630313.202798362188007.42588155630401.912599467
2188143.99228589630534.9773011292188446.30595019630637.693912938
#Sta/Elev= 30
       0 2100.93    18.6 2086.36    32.5 2084.35      36  2082.3    47.6    2074
    56.4 2065.75    65.1 2061.96    88.5  2045.9   109.7 2037.92   132.1 2034.59
   148.8 2035.21   162.32030.882     171 2029.87   181.52030.894   210.9 2032.81
   243.8 2028.92   254.9 2029.79   268.3 2033.75     287 2034.77   302.4 2039.96
   315.1  2041.8   336.2 2047.52   365.8 2048.69   399.7 2054.95   443.8 2060.09
   481.7 2061.59   499.6 2066.01     539 2072.92     577 2078.68   613.1 2081.83
#Mann= 5 ,-1,0
       0      .1       0   162.3    .045       0   181.5      .1       0
  393.77     .06       0  573.77      .1       0
#XS Ineff= 2 , 0
                          257.56          2044.7
Permanent Ineff=
       F       F
Bank Sta=162.3,181.5
XS Rating Curve= 0 ,0
Exp/Cntr(USF)=0,0
Exp/Cntr=0.3,0.1

Type RM Length L Ch R = 1 ,7919    ,188.6,198.8,205.2
XS GIS Cut Line= 2
2187863.85607187630352.8887620132188136.98888054630826.785857405
#Sta/Elev= 30
       0  2096.6    32.7 2081.87    50.2 2075.92    64.7 2072.14    92.7 2062.47
   104.8 2056.66   112.8  2054.5   123.5 2053.15   143.5 2045.36   157.3  2043.8
     182  2038.4   202.5 2037.06   216.9 2033.06   249.6 2030.22   281.6 2031.58
   314.3 2030.92   321.1 2029.39   331.4 2022.64   335.82021.403     342 2020.93
   356.8 2021.39   361.1 2022.26   369.5 2027.18   378.3 2034.93   388.1 2045.97
     390 2046.52   406.6 2047.12   415.8 2051.78   448.2 2059.92     547 2076.13
#Mann= 5 ,-1,0
       0      .1       0   335.8    .045       0   356.8      .1       0
     360     .06       0     540      .1       0
Bank Sta=335.8,356.8
XS Rating Curve= 0 ,0
Exp/Cntr(USF)=0,0
Exp/Cntr=0.3,0.1

Type RM Length L Ch R = 1 ,7720    ,235.3,229,218.8
XS GIS Cut Line= 4
2187797.32372104630394.9091941172187872.02671144630520.970490428
2187792.65478414630820.9496862792187862.68883764630954.014387941
#Sta/Elev= 30
       0 2091.33    13.4    2084    44.5 2069.46    84.1 2052.86   129.3 2040.69
   146.7 2034.81     155 2032.74   171.6 2028.72   204.7 2023.29     213 2020.31
   221.2 2016.29   229.5 2015.92   241.5  2016.3   257.8 2018.48   279.2  2017.5
   283.3 2018.25   293.8  2024.4     304 2026.39   323.3 2027.07   345.4 2026.69
   386.7 2028.54     395 2029.52   411.6 2033.16   432.2 2032.46   440.5 2031.04
   448.8 2034.51   475.2 2039.27   538.5 2053.66   569.2 2061.61   607.2  2072.8
#Mann= 5 ,-1,0
       0      .1       0   221.2    .045       0   241.5      .1       0
  356.53     .06       0  456.53      .1       0
#XS Ineff= 2 , 0
                          277.96         2033.77
Permanent Ineff=
       F       F
Bank Sta=221.2,241.5
XS Rating Curve= 0 ,0
Exp/Cntr(USF)=0,0
Exp/Cntr=0.3,0.1

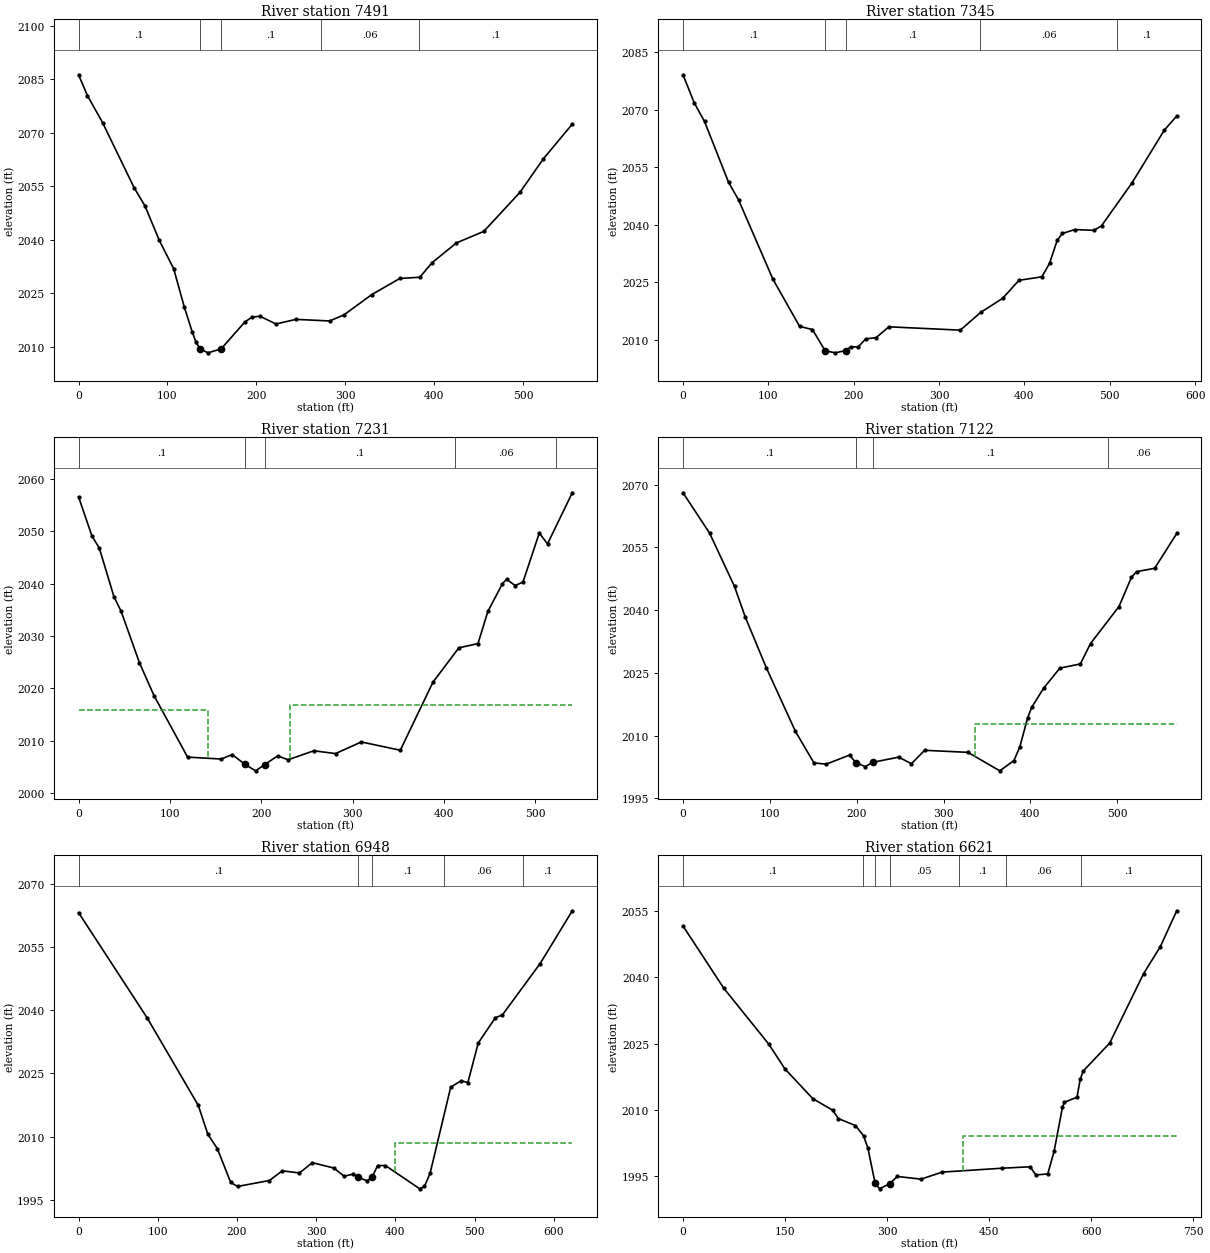
Type RM Length L Ch R = 1 ,7491    ,146.7,146.8,147.1
XS GIS Cut Line= 3
2187643.24880332630467.2777160732187625.74028995630588.670075484
2187823.00287399630973.857369768
#Sta/Elev= 30
       0 2086.27      10 2080.44      27 2072.87    62.5 2054.61    74.7 2049.51
    90.8 2039.86     107 2031.87   119.1 2021.02   127.8 2014.23   132.2 2011.24
   136.7 2009.41   136.7  2009.4   145.6 2008.28   160.5 2009.41   187.2 2016.97
   195.1 2018.28   204.1 2018.55   222.1 2016.37   244.6 2017.67   282.4 2017.22
   298.5 2018.91   329.8 2024.61   361.4 2029.14   383.9 2029.48   397.4  2033.5
     425  2039.1   455.8 2042.33   496.6 2053.31   522.9  2062.7   555.4 2072.43
#Mann= 5 ,-1,0
       0      .1       0   136.7    .045       0   160.5      .1       0
  272.65     .06       0  382.65      .1       0
Bank Sta=136.7,160.5
XS Rating Curve= 0 ,0
Exp/Cntr(USF)=0,0
Exp/Cntr=0.3,0.1

Type RM Length L Ch R = 1 ,7345    ,114.1,113.9,113.8
XS GIS Cut Line= 3
2187488.00665138630499.9602743762187482.17048026630628.356039137
2187680.60029853631032.219081023
#Sta/Elev= 30
       0 2079.05    13.2 2071.72    25.2 2066.89    53.3 2051.08    65.3 2046.36
   105.3 2025.83   136.6 2013.52   151.7 2012.69   166.5 2007.18   178.4 2006.63
   190.4 2007.22   196.3 2008.17   205.2 2008.17   214.1 2010.27   226.3 2010.59
   241.2 2013.41   324.9 2012.54   348.8 2017.17   374.6 2020.84   393.6 2025.52
   420.5 2026.43   429.5 2029.97   438.4  2035.9   444.4 2037.72   459.2 2038.74
   481.5 2038.53   490.4 2039.73   526.1 2050.91     564 2064.65   578.5 2068.31
#Mann= 5 ,-1,0
       0      .1       0   166.5    .045       0   190.4      .1       0
  348.53     .06       0  508.53      .1       0
Bank Sta=166.5,190.4
XS Rating Curve= 0 ,0
Exp/Cntr(USF)=0,0
Exp/Cntr=0.3,0.1

Type RM Length L Ch R = 1 ,7231    ,108.7,109,108.5
XS GIS Cut Line= 3
2187368.88913349630542.460230981 2187367.6640917630655.164075682
2187559.99565277631037.377114235
#Sta/Elev= 30
       0 2056.54    14.7 2049.05    22.7 2046.79    38.7 2037.52    46.7 2034.67
    66.7 2024.88    82.7  2018.6   119.4 2006.89   156.3 2006.52   168.2 2007.38
   182.42005.486   193.9 2004.27   203.82005.459     218 2007.12   229.5 2006.38
   257.6  2008.1   281.4 2007.56   309.6 2009.78   352.3  2008.2   388.1 2021.19
   416.4 2027.73   437.4 2028.55   448.2 2034.69   464.2 2039.98   468.7 2040.81
     478 2039.62   486.6 2040.27   504.5 2049.63   513.5 2047.56   540.6 2057.31
#Mann= 5 ,-1,0
       0      .1       0   182.4    .045       0   203.8      .1       0
  412.71     .06       0  522.71      .1       0
#XS Ineff= 2 , 0
          142.08 2015.83  231.69         2016.78
Permanent Ineff=
       F       F
Bank Sta=182.4,203.8
XS Rating Curve= 0 ,0
Exp/Cntr(USF)=0,0
Exp/Cntr=0.3,0.1

Type RM Length L Ch R = 1 ,7122    ,171.8,173.7,171.3
XS GIS Cut Line= 4
2187242.88746411630579.3322016832187272.99324078630710.478170773
 2187355.4136738630864.646221812 2187480.8876309631091.381408219
#Sta/Elev= 30
       0 2068.03    30.6 2058.38    59.3 2045.63    71.7 2038.31    96.1 2026.12
   129.5 2010.97   150.7 2003.47   164.8 2003.15   191.9 2005.34   198.92003.503
   209.8 2002.58   218.92003.617   248.3 2004.83     263 2003.27   278.2 2006.47
     328 2005.98   364.8 2001.56     381 2004.02   387.7 2007.21   396.8 2014.21
   401.4 2016.71   415.1 2021.27   433.9 2026.11   457.5 2027.11   469.2 2031.99
     502 2040.84   516.3 2047.81   522.2 2049.17   543.1 2049.98   568.5 2058.31
#Mann= 4 ,-1,0
       0      .1       0   198.9    .045       0   218.9      .1       0
  489.37     .06       0
#XS Ineff= 2 , 0
                          336.61         2012.67
Permanent Ineff=
       F       F
Bank Sta=198.9,218.9
XS Rating Curve= 0 ,0
Exp/Cntr(USF)=0,0
Exp/Cntr=0.3,0.1

Type RM Length L Ch R = 1 ,6948    ,327.3,327.3,323.1
XS GIS Cut Line= 3
2187192.69639243630586.3356070342187181.02405018630767.256911925
2187352.60748127631174.621656485
#Sta/Elev= 30
       0 2063.11      87 2038.05   151.2 2017.41   163.2 2010.58   175.2 2007.18
   192.1 1999.15   200.7 1998.21   240.9 1999.61   257.2  2001.9   278.9 2001.41
   295.1 2003.84   322.3 2002.57   335.3 2000.62     347 2001.16   353.1 2000.36
   364.6 1999.53   370.52000.397   377.6 2003.16   387.4 2003.16   430.8 1997.64
   436.7 1998.21   443.8 2001.32   469.8 2021.72   482.9 2023.26   491.5 2022.83
   504.6 2032.21   526.3 2038.22     535 2038.84   582.7 2051.02   623.3 2063.54
#Mann= 5 ,-1,0
       0      .1       0   353.1    .045       0   370.5      .1       0
   461.3     .06       0   561.3      .1       0
#XS Ineff= 2 , 0
                          399.28         2008.62
Permanent Ineff=
       F       F
Bank Sta=353.1,370.5
XS Rating Curve= 0 ,0
Exp/Cntr(USF)=0,0
Exp/Cntr=0.3,0.1

Type RM Length L Ch R = 1 ,6621    ,205,207.5,210.2
XS GIS Cut Line= 3
2187143.67255498630598.0079492852187003.60444797630823.284154729
2187181.02405018631248.157412667
#Sta/Elev= 30
       0 2051.66      60 2037.55   126.2 2024.87   149.7 2019.31   190.7 2012.56
   219.8 2009.95   228.5 2008.03   253.4 2006.45   265.3 2004.16   271.7 2001.37
   282.4 1993.35     289 1992.12   303.8  1993.3     315 1994.93   349.8 1994.31
   380.9 1995.91   468.7 1996.79   510.1 1997.12   518.7 1995.27   536.1 1995.49
   545.4 2000.61   557.7 2010.59   560.7 2011.74   579.1 2012.89   583.8  2016.9
   588.1 2018.79   627.1 2025.13   676.9 2040.85   701.4 2046.94   725.7 2055.11
#Mann= 7 ,-1,0
       0      .1       0  265.27     .05       0   282.4    .045       0
   303.8     .05       0  405.27      .1       0  475.27     .06       0
  585.27      .1       0
#XS Ineff= 2 , 0
                          410.93         2004.04
Permanent Ineff=
       F       F
Bank Sta=282.4,303.8
XS Rating Curve= 0 ,0
Exp/Cntr(USF)=0,0
Exp/Cntr=0.3,0.1

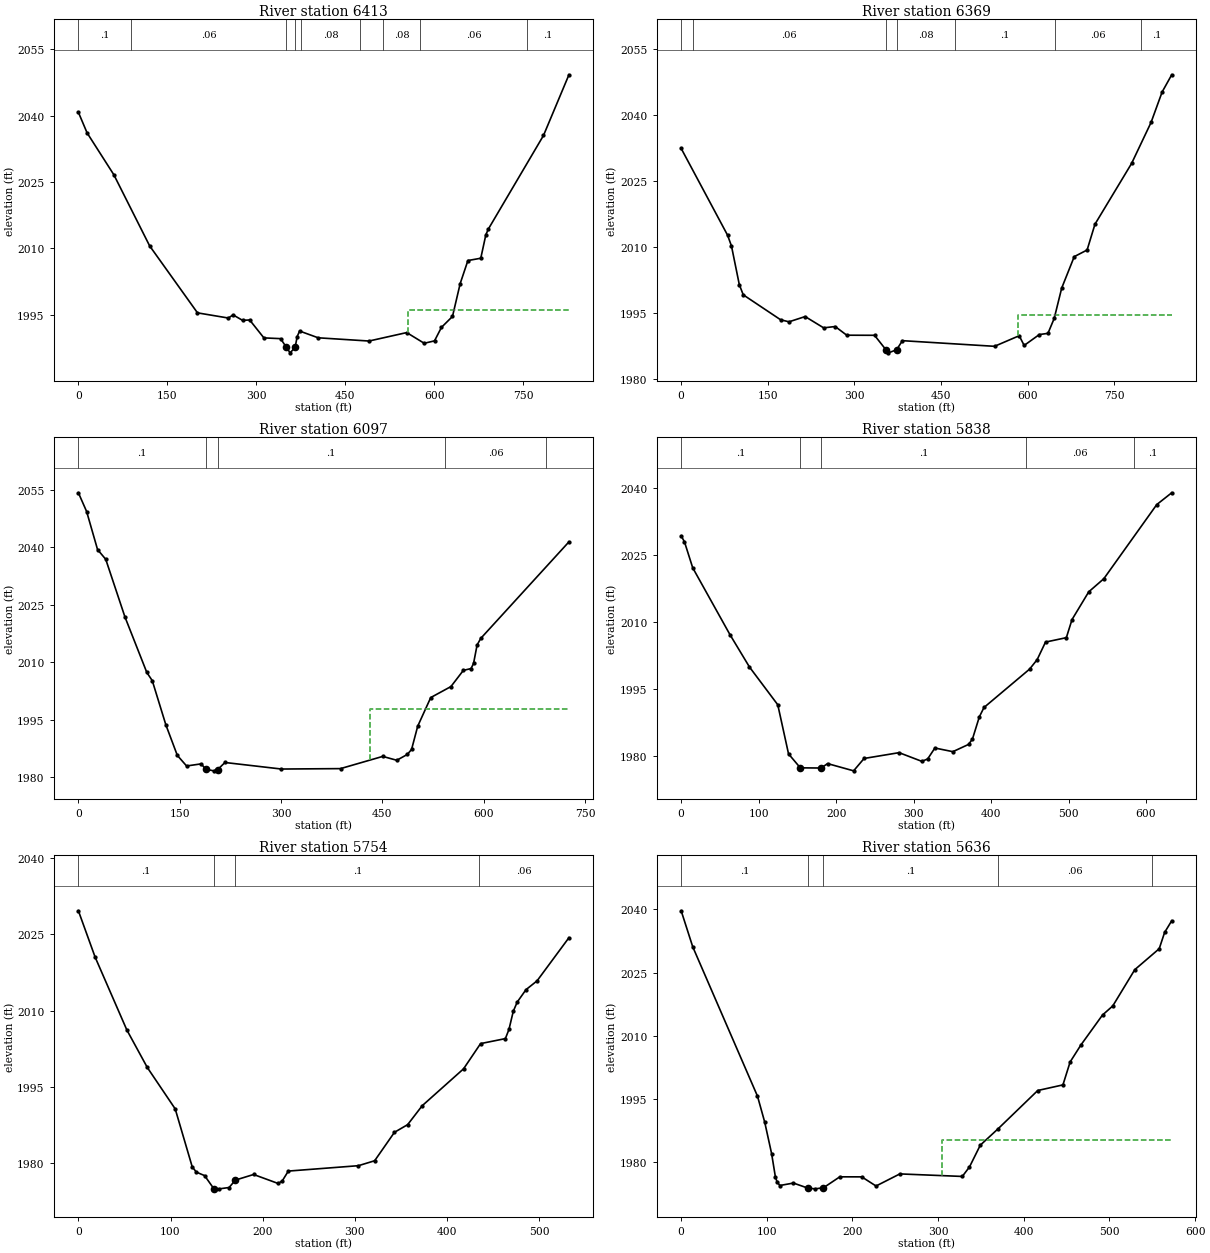
Type RM Length L Ch R = 1 ,6413    ,44.1,44.1,44.5
BEGIN DESCRIPTION:
Structure XS 3
END DESCRIPTION:
XS GIS Cut Line= 6
2186913.78807188630585.8642233492186813.62759806630718.581298782
2186818.96474587 630932.067211012186875.89432246631109.972137865
2186925.76741042631229.639000539 2186998.2700669631338.579085778
#Sta/Elev= 30
       0 2040.78    14.7 2036.12    59.8 2026.66   120.2 2010.57   200.9 1995.43
   252.9 1994.26   260.9 1994.97   276.9 1993.74   288.9 1993.82   312.9 1989.77
     341  1989.6     3511987.613   357.1 1986.39   365.51987.603   369.1 1990.08
   373.1 1991.32   404.5 1989.79   490.2 1989.06   553.8 1990.97   583.3 1988.55
   600.7  1989.1   612.4 1992.15     631 1994.62     644 2002.06     657 2007.26
   678.7 2007.78   687.3  2013.1   691.7 2014.43   784.5 2035.54   827.4 2049.26
#Mann= 9 ,-1,0
       0      .1       0   89.02     .06       0     351    .045       0
   365.5     .06       0  375.79     .08       0  474.53      .1       0
  514.53     .08       0  576.86     .06       0  756.51      .1       0
#XS Ineff= 2 , 0
                          555.96         1996.17
Permanent Ineff=
       F       F
Bank Sta=351,365.5
XS Rating Curve= 0 ,0
Exp/Cntr(USF)=0,0
Exp/Cntr=0.3,0.1

Type RM Length L Ch R = 1 ,6369    ,277,272.2,266
BEGIN DESCRIPTION:
Structure XS 2
END DESCRIPTION:
XS GIS Cut Line= 6
2186869.81518414630588.0834396742186769.65471032630720.800515108
2186774.99185813630934.2864273352186831.92143472 631112.19135419
2186881.79452268631231.8582168642186966.77336928631358.945487739
#Sta/Elev= 30
       0 2032.34    80.3 2012.67    87.1 2010.21   100.7 2001.43   107.5 1999.13
   172.2 1993.47   186.7 1993.01   214.7  1994.2   246.7 1991.64   266.7 1991.94
   286.7 1989.97   334.8 1989.95   354.3 1986.71   358.9 1985.97     3731986.666
   383.1 1988.73   542.6 1987.45   585.3 1989.85   593.9 1987.65   620.2 1990.12
   635.1 1990.39   645.9 1993.77   658.9 2000.66   680.6 2007.79   702.9  2009.3
   716.5 2015.15   779.9 2028.93   813.6 2038.23   832.8 2045.15   849.4 2049.05
#Mann= 7 ,-1,0
       0      .1       0      20     .06       0   354.3    .045       0
     373     .08       0  474.53      .1       0  646.86     .06       0
  796.51      .1       0
#XS Ineff= 2 , 0
                          583.39          1994.6
Permanent Ineff=
       F       F
Bank Sta=354.3,373
XS Rating Curve= 0 ,0
Exp/Cntr(USF)=0,0
Exp/Cntr=0.3,0.1

Type RM Length L Ch R = 1 ,6097    ,264,259.2,252.7
BEGIN DESCRIPTION:
Structure XS 1
END DESCRIPTION:
XS GIS Cut Line= 3
 2186372.1707608630932.4934068442186513.07146287630954.909427628
 2186882.9358058631406.432131988
#Sta/Elev= 30
       0 2054.29    12.2  2049.4    28.4 2039.45    40.5 2036.92    68.9 2021.88
   101.3 2007.37   109.4 2005.22   129.6 1993.64   146.5  1985.7   160.2 1982.94
   181.8 1983.49   188.71982.074   200.5 1981.67   206.2 1981.99     217 1983.85
   300.7 1982.14   388.1 1982.25   450.6 1985.44   471.4 1984.43   486.9 1985.94
   493.3 1987.25   502.4 1993.33   521.7 2000.81   551.6 2003.68     570 2007.91
   581.4 2008.38   585.1 2009.73   590.3 2014.52   595.7 2016.25   726.3 2041.47
#Mann= 5 ,-1,0
       0      .1       0   188.7    .045       0   206.2      .1       0
  542.67     .06       0  692.67      .1       0
#XS Ineff= 2 , 0
                          431.33         1997.94
Permanent Ineff=
       F       F
Bank Sta=188.7,206.2
XS Rating Curve= 0 ,0
Exp/Cntr(USF)=0,0
Exp/Cntr=0.3,0.1

Type RM Length L Ch R = 1 ,5838    ,82.3,83.8,85.9
XS GIS Cut Line= 3
  2186284.107822631156.653614682 2186641.1630102631270.334862943
2186833.30033121631443.258451847
#Sta/Elev= 30
       0  2029.3     4.3 2027.93    14.9 2022.14      63 2007.17    88.2 1999.92
   124.7 1991.48   138.6 1980.48   153.81977.362   180.6 1977.32     189 1978.31
   222.6 1976.69   236.1 1979.46   281.3 1980.76   310.7 1978.81   318.2 1979.36
   327.5  1981.8   350.7 1980.98   370.9  1982.6     376 1983.81   384.9 1988.79
   390.9 1990.87   449.7 1999.45   459.5 2001.58   470.3 2005.51   497.2  2006.5
   504.5 2010.55   526.1 2016.76   545.6  2019.7   613.9 2036.29   633.2 2038.93
#Mann= 5 ,-1,0
       0      .1       0   153.8    .045       0   180.6      .1       0
  444.72     .06       0  584.72      .1       0
Bank Sta=153.8,180.6
XS Rating Curve= 0 ,0
Exp/Cntr(USF)=0,0
Exp/Cntr=0.3,0.1

Type RM Length L Ch R = 1 ,5754    ,119,117.4,116.2
XS GIS Cut Line= 3
2186268.80160586631216.2332156092186507.68475496631331.387143891
2186756.36823838 631429.39048711
#Sta/Elev= 30
       0 2029.65    18.2 2020.53    52.6 2006.23    74.8 1998.86   105.1 1990.72
   123.6 1979.32   128.1 1978.29     137 1977.61   146.91975.071     153 1975.01
   163.6 1975.27   170.41976.724   190.2 1977.83   216.9 1976.06   221.3 1976.57
   227.9  1978.5     304 1979.56   321.6 1980.53   343.1 1986.12   357.4 1987.62
   373.2 1991.34   418.1 1998.59   436.6 2003.55   463.5 2004.53   467.4 2006.33
   472.1 2009.91   476.4 2011.72   485.9 2014.15   497.9 2015.88   532.5 2024.36
#Mann= 4 ,-1,0
       0      .1       0   146.9    .045       0   170.4      .1       0
  435.19     .06       0
Bank Sta=146.9,170.4
XS Rating Curve= 0 ,0
Exp/Cntr(USF)=0,0
Exp/Cntr=0.3,0.1

Type RM Length L Ch R = 1 ,5636    ,110.1,113.8,116.3
BEGIN DESCRIPTION:
Disconnected without IFA
END DESCRIPTION:
XS GIS Cut Line= 2
2186215.25861531631345.5886470042186761.24883583631518.512235908
#Sta/Elev= 30
       0 2039.66    13.5 2031.12    89.1  1995.7    97.5 1989.57   105.6 1982.06
   110.1 1976.43   111.9 1975.43   115.1 1974.51   131.1 1975.09   147.8  1973.9
   156.2 1973.72   166.1 1973.97   185.2 1976.57   210.8 1976.56   227.5 1974.39
   255.3 1977.26   328.2 1976.66   336.6 1978.91   349.2 1984.07     370 1987.96
   416.3 1997.04   445.7 1998.37   454.1 2003.81   466.7 2007.84   491.9 2014.94
   503.9  2017.1   529.6  2025.7   558.1 2030.66   564.4 2034.52   572.7 2037.29
#Mann= 5 ,-1,0
       0      .1       0   147.8    .045       0   166.1      .1       0
     370     .06       0     550      .1       0
#XS Ineff= 2 , 0
                          304.92         1985.33
Permanent Ineff=
       F       F
Bank Sta=147.8,166.1
XS Rating Curve= 0 ,0
Exp/Cntr(USF)=0,0
Exp/Cntr=0.3,0.1

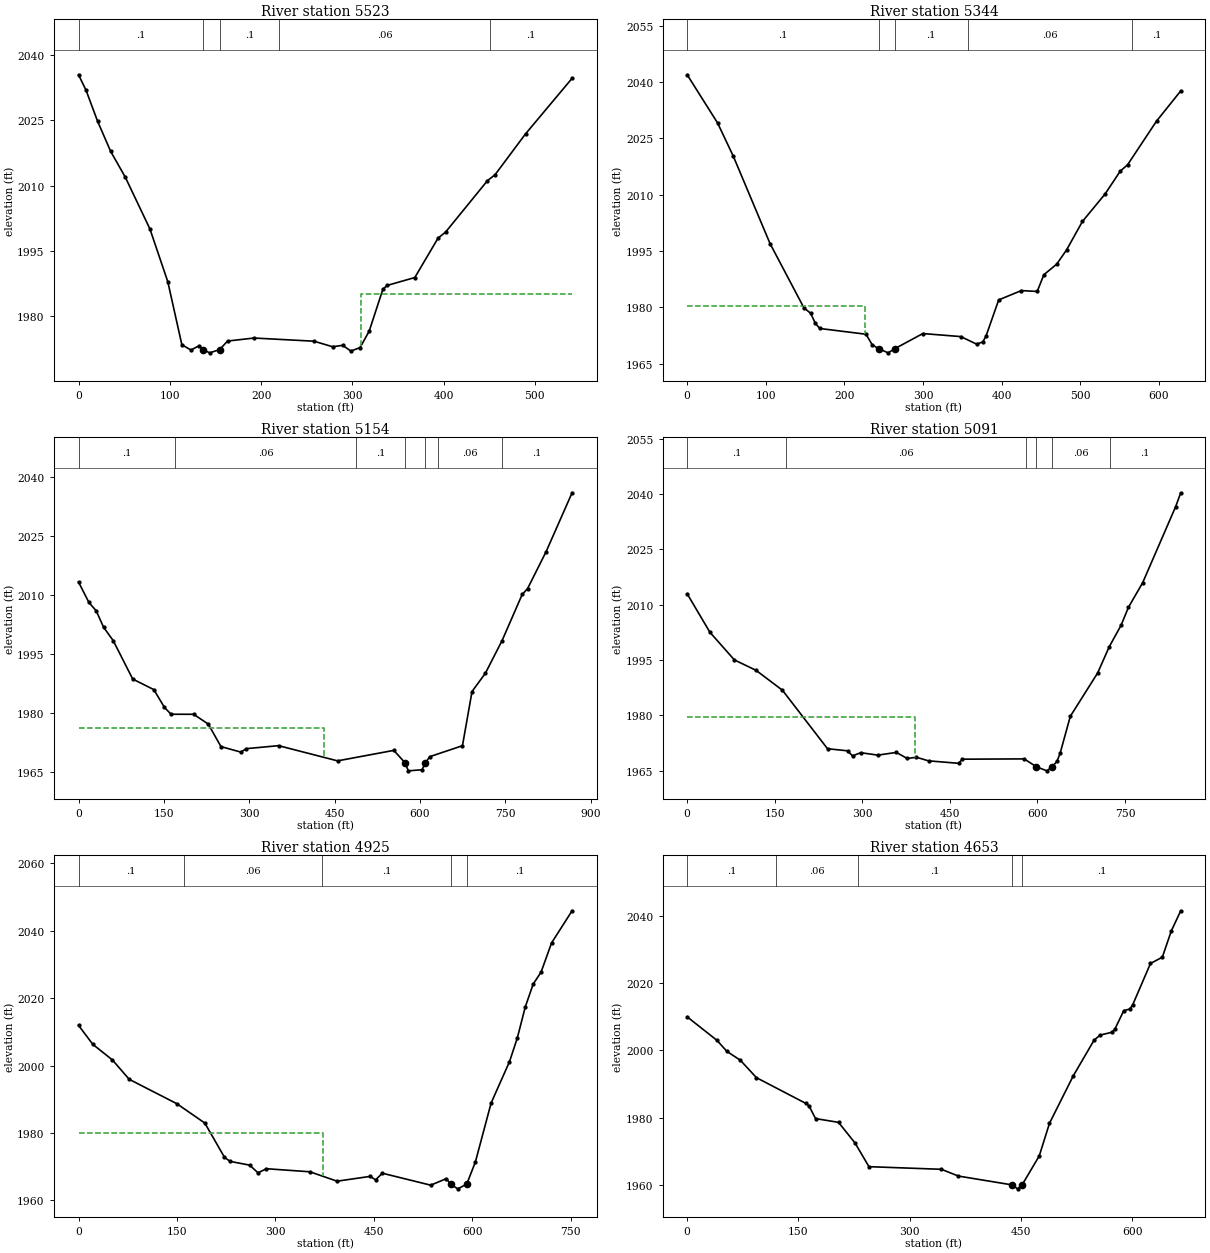
Type RM Length L Ch R = 1 ,5523    ,184.4,179,174
BEGIN DESCRIPTION:
Disconnected without IFA
END DESCRIPTION:
XS GIS Cut Line= 3
2186197.64602755631406.4321319882186493.85773076631628.991195485
2186657.17445362631677.025525736
#Sta/Elev= 30
       0 2035.45     8.2 2031.91    20.9 2024.77    35.2 2017.86    51.2 2011.95
    78.2 2000.06    97.8 1987.93   113.2 1973.47   123.2 1972.25   132.3 1973.27
   136.31972.327   143.8 1971.61   154.6 1972.37   163.3 1974.32   192.3 1975.01
     258 1974.28   278.3 1973.01   289.4 1973.33   298.4 1972.01   308.4 1972.82
   318.4 1976.58   333.4 1986.19     338 1987.08   368.4  1988.9   393.8 1997.93
   402.1 1999.33     448 2011.14   456.3  2012.5   489.7 2021.88   540.7 2034.64
#Mann= 5 ,-1,0
       0      .1       0   136.3    .045       0   154.6      .1       0
     220     .06       0   450.5      .1       0
#XS Ineff= 2 , 0
                          309.29         1985.15
Permanent Ineff=
       F       F
Bank Sta=136.3,154.6
XS Rating Curve= 0 ,0
Exp/Cntr(USF)=0,0
Exp/Cntr=0.3,0.1

Type RM Length L Ch R = 1 ,5344    ,199.4,190,178
BEGIN DESCRIPTION:
Structure XS 4
END DESCRIPTION:
XS GIS Cut Line= 4
 2186111.1842331631476.8824830232186229.60026857631658.473301883
  2186407.868773631674.7797444192186634.18886201631724.694587428
#Sta/Elev= 30
       0 2041.97    38.6 2029.15    58.7 2020.24   105.4 1996.96   148.3 1979.91
     157 1978.39   162.9 1975.75   168.6 1974.35   227.4 1972.82   235.4 1969.96
   243.81968.951   255.5 1967.86     2641968.967   299.7    1973   347.9 1972.19
     368 1970.19   375.8 1970.76   379.9 1972.26   396.1 1981.97   424.9 1984.45
   445.1 1984.22   453.5 1988.67   469.8 1991.48   482.4 1995.28   502.6 2002.88
   531.3 2010.17   550.7 2016.29     560 2017.98   596.8 2029.62   627.6 2037.67
#Mann= 5 ,-1,0
       0      .1       0   243.8    .045       0     264      .1       0
  356.79     .06       0   565.8      .1       0
#XS Ineff= 2 , 0
          225.68 1980.42  416.97         1980.79
Permanent Ineff=
       F       F
Bank Sta=243.8,264
XS Rating Curve= 0 ,0
Exp/Cntr(USF)=0,0
Exp/Cntr=0.3,0.1

Type RM Length L Ch R = 1 ,5154    ,63.4,62.6,62.8
BEGIN DESCRIPTION:
Structure XS 3
END DESCRIPTION:
XS GIS Cut Line= 6
2185815.18376502632095.0846980452186052.08890768632004.817348254
2186261.02270575631900.3349107012186290.10498179631871.367935095
2186382.91820723631788.3390301862186592.95186323631831.313203194
#Sta/Elev= 30
       0 2013.32    18.2 2008.13      31 2006.01    43.9 2001.85      61 1998.38
    95.2 1988.62   132.4 1985.92     151 1981.38   162.6 1979.66   202.2 1979.65
   227.9 1977.16   250.2 1971.43   285.1 1970.02   294.9  1970.9   351.4 1971.66
   455.1 1967.79   553.9 1970.46   573.7 1967.29   579.4 1965.25   603.4 1965.52
   609.4 1967.24   616.9 1968.85   674.5 1971.65   691.3 1985.45   714.8 1990.11
   744.1 1998.41   779.4 2010.15   788.9 2011.65   821.5 2021.07   867.1 2036.05
#Mann= 7 ,-1,0
       0      .1       0     170     .06       0  487.14      .1       0
   573.7    .045       0   609.4      .1       0  632.05     .06       0
  743.47      .1       0
#XS Ineff= 2 , 0
          431.69 1976.25
Permanent Ineff=
       F       F
Bank Sta=573.7,609.4
XS Rating Curve= 0 ,0
Exp/Cntr(USF)=0,0
Exp/Cntr=0.3,0.1

Type RM Length L Ch R = 1 ,5091    ,155.2,165.9,176.5
BEGIN DESCRIPTION:
Structure XS 2
END DESCRIPTION:
XS GIS Cut Line= 6
 2185823.9027414632137.5683014282186090.14595664632034.699592785
2186307.05286182631942.5085950332186337.47460432631916.890285566
2186409.52609969631843.2376458472186588.75202722 631872.14742107
#Sta/Elev= 30
       0 2012.93    38.9  2002.5    80.9 1994.99     118 1992.17   163.2 1986.77
   240.4 1970.91   274.7 1970.34   283.3 1968.97   297.3 1969.83   326.7 1969.17
   358.4 1969.91   376.8 1968.26   392.8 1968.59   413.4 1967.62   465.2 1966.95
   471.3 1968.07   577.3 1968.15   598.21966.018   616.2 1964.91   624.8 1965.96
   633.4 1967.45     639 1969.73   656.3 1979.69   703.2 1991.47   723.1 1998.59
   743.3 2004.39   755.9 2009.26   780.2 2015.91   836.8 2036.57   845.5 2040.33
#Mann= 6 ,-1,0
       0      .1       0     170     .06       0  580.89      .1       0
   598.2    .045       0   624.8     .06       0  723.92      .1       0
#XS Ineff= 2 , 0
           389.8 1979.53
Permanent Ineff=
       F       F
Bank Sta=598.2,624.8
XS Rating Curve= 0 ,0
Exp/Cntr(USF)=0,0
Exp/Cntr=0.3,0.1

Type RM Length L Ch R = 1 ,4925    ,263.1,271.7,276.5
BEGIN DESCRIPTION:
Structure XS 1
END DESCRIPTION:
XS GIS Cut Line= 3
2185827.78168462632144.5596735142186128.79682086632032.479569595
2186559.50464877632051.693301695
#Sta/Elev= 30
       0 2011.91    21.8 2006.27    51.6 2001.66    77.2 1995.91   149.8 1988.67
   192.5 1982.92   222.4 1972.79   230.9 1971.56   260.8 1970.44   273.6 1968.16
   286.4 1969.38   352.6 1968.47   394.1 1965.68   444.7 1967.11   452.7 1966.07
   463.1 1968.04   536.8  1964.5   560.8 1966.45   567.1 1964.76   578.1 1963.41
   591.71964.795   604.9 1971.38   628.9 1988.88   656.9 2001.13   668.9 2008.23
   680.9 2017.34     693 2024.16     705 2027.69     721 2036.36   752.3  2045.9
#Mann= 5 ,-1,0
       0      .1       0     160     .06       0   371.2      .1       0
   567.1    .045       0   591.7      .1       0
#XS Ineff= 2 , 0
          373.04 1980.05
Permanent Ineff=
       F       F
Bank Sta=567.1,591.7
XS Rating Curve= 0 ,0
Exp/Cntr(USF)=0,0
Exp/Cntr=0.3,0.1

Type RM Length L Ch R = 1 ,4653    ,315.9,311.8,304.4
XS GIS Cut Line= 4
2185867.81029316632259.8420661172186083.96477929632157.368828248
2186282.50667766632298.2695303182186465.03713261632295.067241634
#Sta/Elev= 30
       0 2009.95    40.2 2002.95    53.5 1999.69    71.6 1997.06    93.4 1991.86
   159.8 1984.23   164.2 1983.48     173  1979.7     204 1978.58   226.2 1972.45
     245  1965.4   342.6 1964.62   365.5 1962.61   437.2 1960.01   445.5 1958.81
   451.5 1960.03   474.5 1968.59   488.3  1978.3   520.3 1992.39   548.3 2002.98
   556.4 2004.51   572.4 2005.37   576.4 2006.28   588.4 2011.79   596.4 2012.27
   600.4  2013.5   624.4 2025.82   640.4 2027.69   652.4 2035.45   665.2 2041.49
#Mann= 5 ,-1,0
       0      .1       0     120     .06       0     230      .1       0
   437.2    .045       0   451.5      .1       0
Bank Sta=437.2,451.5
XS Rating Curve= 0 ,0
Exp/Cntr(USF)=0,0
Exp/Cntr=0.3,0.1

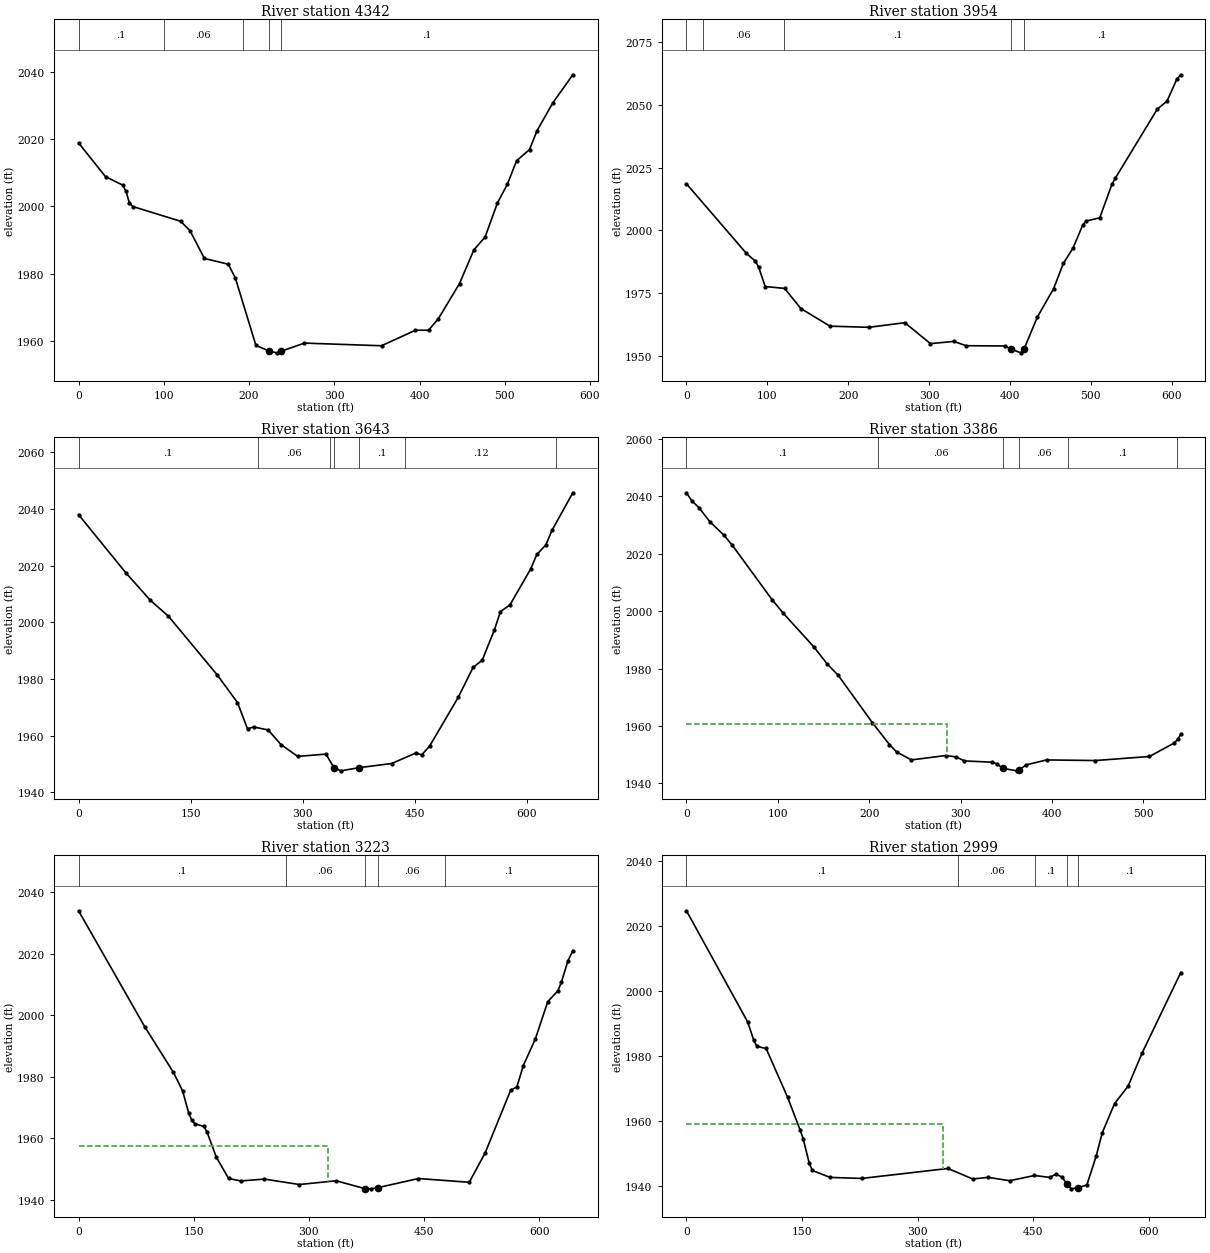
Type RM Length L Ch R = 1 ,4342    ,385.7,387.3,387.3
XS GIS Cut Line= 4
2185880.61944789632552.8514806482186063.14990285632557.654913674
2186287.31011068632516.0251607892186442.62111183632448.777098438
#Sta/Elev= 30
       0 2018.95    31.6 2008.89    51.6  2006.4    55.6  2004.6    59.6 2001.03
    63.6 1999.99   119.6 1995.61   130.7 1992.81   147.6 1984.52   175.6 1982.81
   183.9 1978.71     208 1958.66   223.2 1956.94   232.5  1956.4   237.71956.893
     265  1959.3   355.4 1958.51   395.2 1963.14   410.6 1963.14   422.2 1966.63
   446.9 1977.04   463.8 1987.11   476.9 1990.89   491.3 2001.02   503.1 2006.67
   513.8 2013.61     529 2016.97   537.9 2022.61   556.4  2030.9   579.8 2039.24
#Mann= 5 ,-1,0
       0      .1       0     100     .06       0  192.59      .1       0
   223.2    .045       0   237.7      .1       0
Bank Sta=223.2,237.7
XS Rating Curve= 0 ,0
Exp/Cntr(USF)=0,0
Exp/Cntr=0.3,0.1

Type RM Length L Ch R = 1 ,3954    ,313.3,310.9,306.7
XS GIS Cut Line= 2
2185863.00686013632908.3055245072186473.04285432632874.681493331
#Sta/Elev= 30
       0 2018.55    74.2  1990.8    85.3 1987.73    89.3 1985.33    97.3 1977.65
   121.4 1976.89   141.4 1968.89   177.4 1961.87   225.5 1961.41   269.9 1963.25
   301.6 1954.92   330.6  1955.8   345.7 1954.09   393.8 1953.98   401.8 1952.65
   413.4 1951.25   417.11952.612   433.8 1965.51   453.9 1976.81   465.9 1986.83
   477.9 1992.97   489.9 2002.12   493.9 2003.71   510.9    2005     526 2018.34
     530 2020.69   582.1 2048.28   594.1 2051.47   606.1 2060.13     611 2061.94
#Mann= 5 ,-1,0
       0      .1       0      20     .06       0     120      .1       0
   401.8    .045       0   417.1      .1       0
Bank Sta=401.8,417.1
XS Rating Curve= 0 ,0
Exp/Cntr(USF)=0,0
Exp/Cntr=0.3,0.1

Type RM Length L Ch R = 1 ,3643    ,258.9,257.7,252.1
XS GIS Cut Line= 4
2185841.99167506633232.0099413682186113.52425787633179.970763296
 2186306.4548655633168.0185738952186495.65785908633135.462413829
#Sta/Elev= 30
       0    2038    63.3 2017.48    95.9 2007.84   120.3 2002.17   185.5 1981.51
   212.8 1971.68   226.2 1962.44   234.4 1963.08   253.8 1962.03     271 1956.89
   293.4  1952.7   331.2  1953.5     342 1948.72   351.3  1947.6   375.3 1948.71
   419.4 1950.19   451.4  1953.9   459.5 1953.24   470.3 1956.43   508.4 1973.55
   528.3  1984.1   540.5 1986.66   556.8 1997.35   564.9 2003.81   577.6 2006.15
   605.5 2018.92   613.6 2023.96   625.8 2027.37   633.9 2032.48   661.8 2045.73
#Mann= 7 ,-1,0
       0      .1       0     240     .06       0  336.47      .1       0
     342    .045       0   375.3      .1       0  436.47     .12       0
  639.77      .1       0
Bank Sta=342,375.3
XS Rating Curve= 0 ,0
Exp/Cntr(USF)=0,0
Exp/Cntr=0.3,0.1

Type RM Length L Ch R = 1 ,3386    ,163.1,162.6,161.9
XS GIS Cut Line= 3
2185866.52990577633456.6233914912186153.18968468633438.247764637
2186378.59737409633321.868794565
#Sta/Elev= 30
       0 2041.24     5.7 2038.53    13.7 2036.04    25.7 2031.15    40.9 2026.51
      50 2023.04    93.8 2003.97   105.9 1999.31   139.4 1987.57     154 1981.62
     166  1977.7   203.6 1961.13   222.1 1953.56   230.1 1950.95   246.1 1948.19
   283.5 1949.71   295.1 1949.25   304.1 1947.84   334.8  1947.4   340.1 1946.78
     3461945.272   361.5 1944.39   364.31944.714   371.6 1946.45   394.1 1948.19
   447.6 1947.98   506.7 1949.39   533.7 1954.06   538.2 1955.55   540.9 1957.18
#Mann= 6 ,-1,0
       0      .1       0     210     .06       0     346    .045       0
   364.3     .06       0  417.25      .1       0  537.25     .12       0
#XS Ineff= 2 , 0
          285.25 1960.58
Permanent Ineff=
       F       F
Bank Sta=346,364.3
XS Rating Curve= 0 ,0
Exp/Cntr(USF)=0,0
Exp/Cntr=0.3,0.1

Type RM Length L Ch R = 1 ,3223    ,215.5,224.1,223.7
XS GIS Cut Line= 4
 2185900.8310759633581.5776540942186260.99336222633566.877152612
2186292.84444877633547.2764839682186530.50255607633483.574310876
#Sta/Elev= 30
       0  2033.9    86.5 1996.11   123.4 1981.49   135.5 1975.42   143.5 1968.18
   147.5  1965.9   151.5  1964.7   163.5 1963.83   167.5 1961.94   179.5 1953.83
   195.5 1946.94   211.5 1946.14   242.1 1946.75   287.6 1944.98   335.6  1946.2
   372.81943.661   381.5 1943.58   389.91943.958   442.7 1946.93     509 1945.71
   529.7 1955.27   562.8 1975.55   571.1 1976.74   579.4 1983.63     595 1992.22
   611.3 2004.41   624.4 2007.88   629.1 2010.78   637.4 2017.54   643.9 2020.96
#Mann= 5 ,-1,0
       0      .1       0     270     .06       0   372.8    .045       0
   389.9     .06       0  477.86      .1       0
#XS Ineff= 2 , 0
          325.14 1957.41
Permanent Ineff=
       F       F
Bank Sta=372.8,389.9
XS Rating Curve= 0 ,0
Exp/Cntr(USF)=0,0
Exp/Cntr=0.3,0.1

Type RM Length L Ch R = 1 ,2999    ,58.2,57.7,57.6
XS GIS Cut Line= 4
2185924.79601849633690.9965731762186257.31823685633700.406707747
2186483.53903761633710.4302445792186559.90355904633679.580997313
#Sta/Elev= 30
       0 2024.65    79.5 1990.47    87.4 1984.84    91.4 1982.98   103.4 1982.33
   131.4 1967.27   147.4 1957.36   151.4 1954.64   159.4 1947.07   163.4 1944.83
   186.5  1942.7   227.5 1942.39   339.5 1945.45   371.6 1942.22   391.6 1942.72
   419.6 1941.68   451.6 1943.29   471.6 1942.71   479.7 1943.73   487.7 1942.78
   493.8 1940.64   499.7 1939.19   508.7  1939.6   519.7 1940.38   531.7 1949.16
   539.7 1956.44   555.7 1965.41   573.1 1970.69   591.3 1980.88   641.5 2005.63
#Mann= 5 ,-1,0
       0      .1       0  352.66     .06       0  452.66      .1       0
   493.8    .045       0   508.7      .1       0
#XS Ineff= 2 , 0
          332.79 1959.26
Permanent Ineff=
       F       F
Bank Sta=493.8,508.7
XS Rating Curve= 0 ,0
Exp/Cntr(USF)=0,0
Exp/Cntr=0.3,0.1