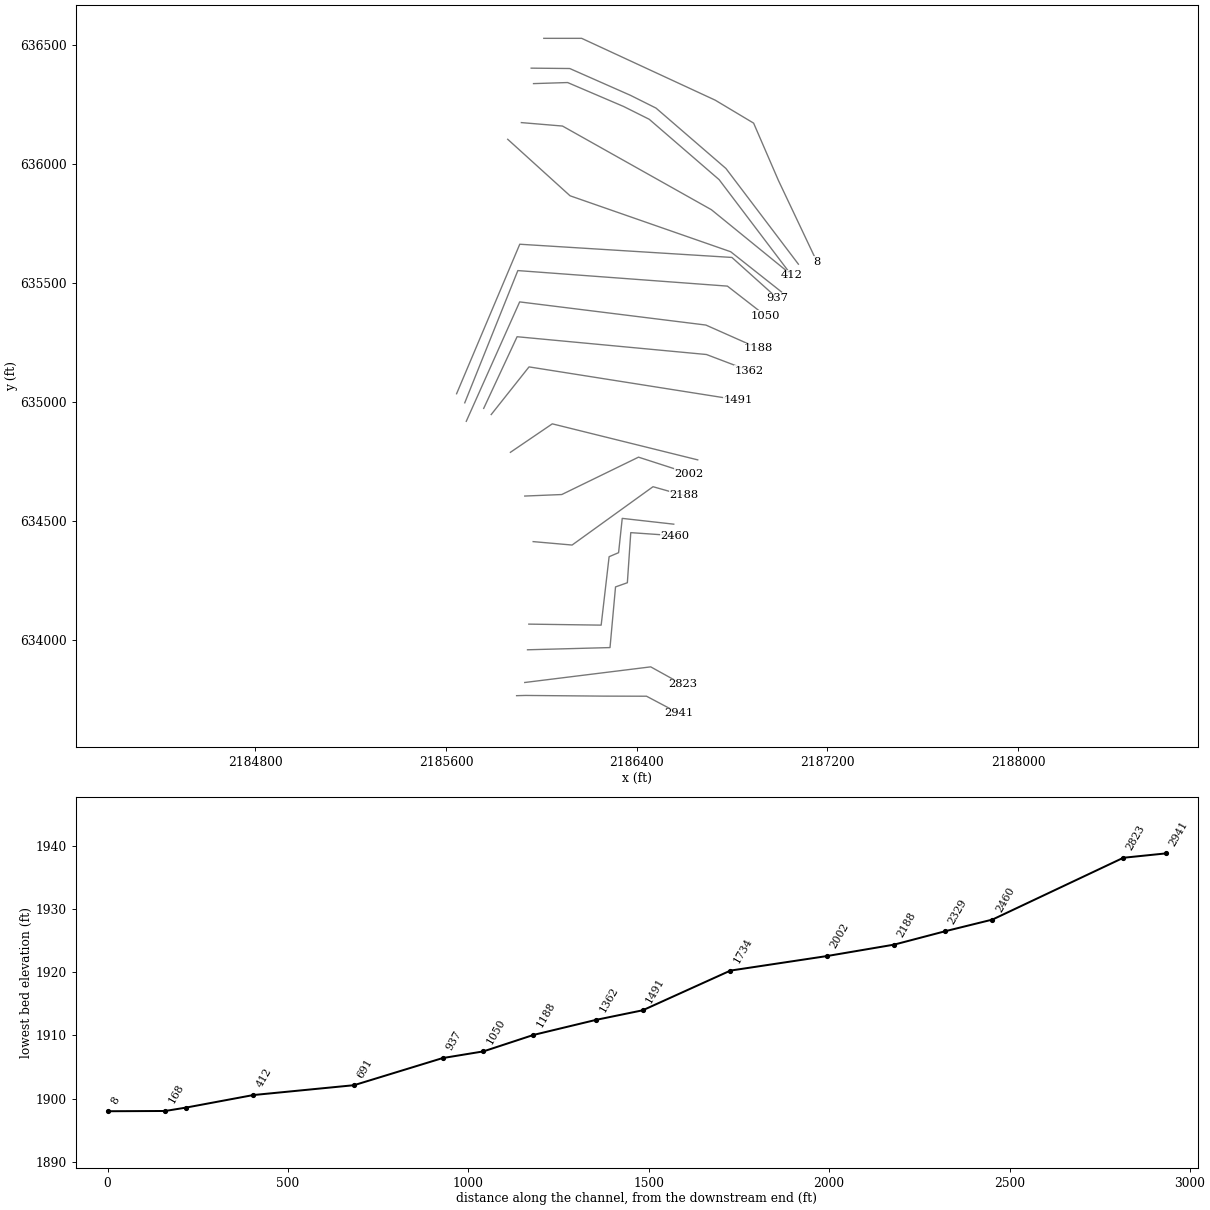
HEC-RAS study MFRFBUCKRV.prj: MFRFBUCKRV

--- MFRFBUCKRV.g01 (geometry) --- (continued)

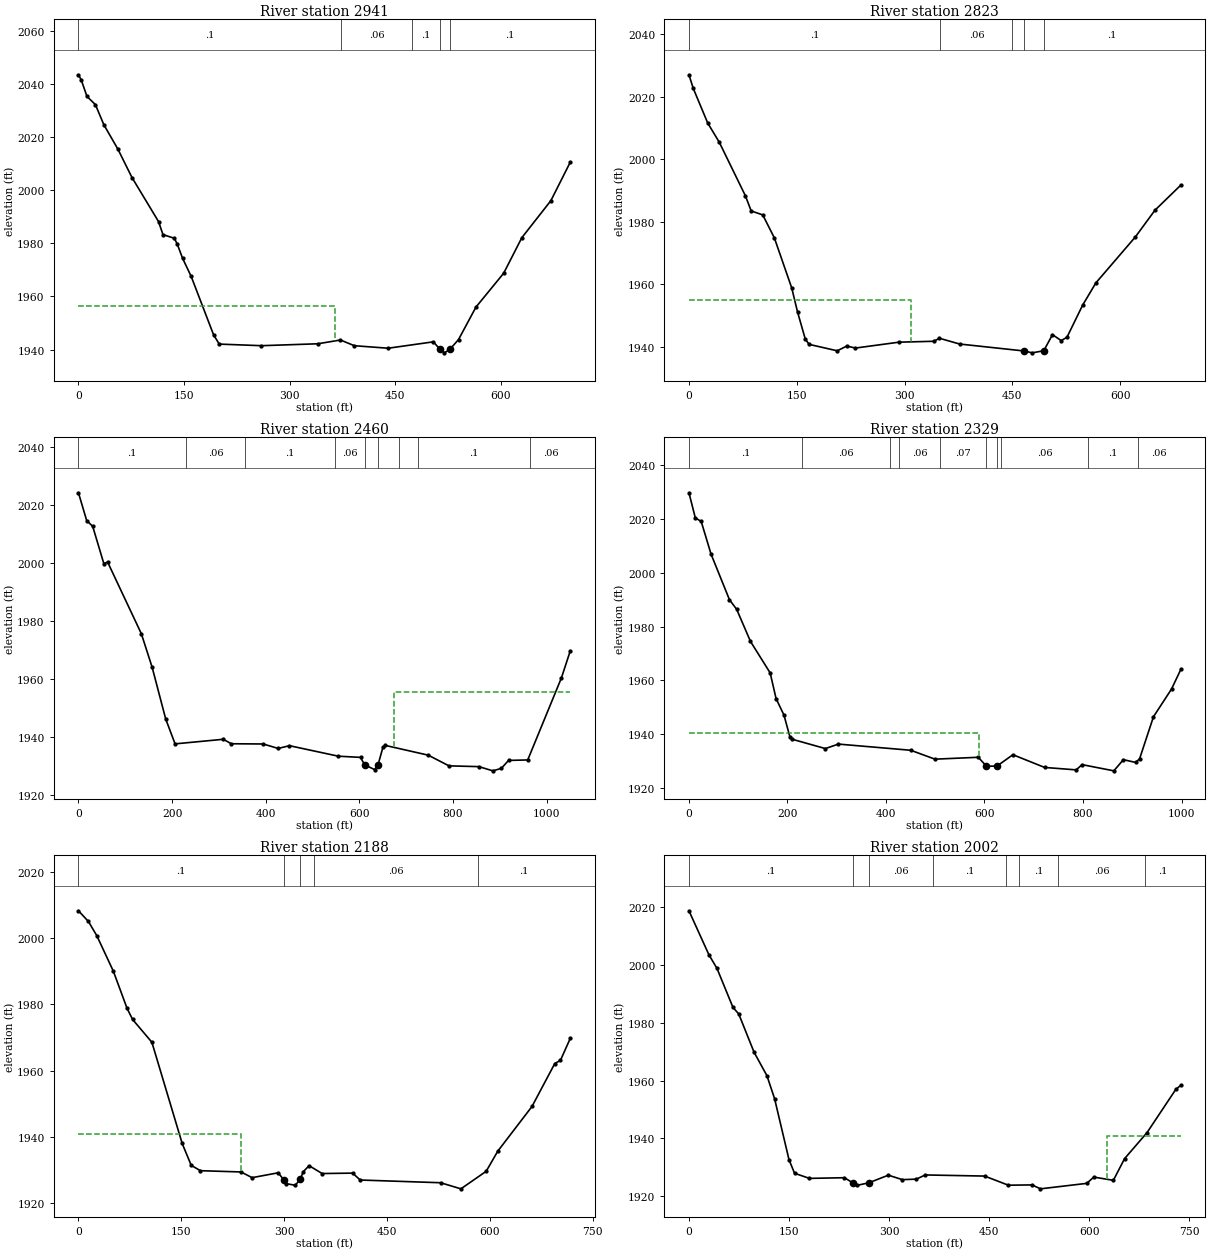
Type RM Length L Ch R = 1 ,2941    ,116.3,117.9,118.8
XS GIS Cut Line= 5
2185896.05048649633767.2176985942185934.41294674633768.163371969
2186259.76832043 633765.333922632186441.01996749633764.917747319
2186577.11723653633692.866251942
#Sta/Elev= 30
       0 2043.44     4.1 2041.41    12.1  2035.3    24.1 2032.21    36.1 2024.64
    56.1 2015.43    76.1 2004.76   113.8  1988.2   120.1 1983.29   136.1 1981.92
   140.1 1979.93   148.1  1974.3   160.1 1967.62   192.1 1945.53   200.1 1942.08
   260.1 1941.48   340.1  1942.2   372.3 1943.62   392.1 1941.47   440.2 1940.53
   504.3 1942.93   513.51940.214   520.1 1938.79   527.91940.122   540.1 1943.78
   564.9 1956.01   604.3 1968.76   630.1 1982.13   671.4 1996.08     699 2010.58
#Mann= 5 ,-1,0
       0      .1       0  373.74     .06       0  473.74      .1       0
   513.5    .045       0   527.9      .1       0
#XS Ineff= 2 , 0
          364.66 1956.57
Permanent Ineff=
       F       F
Bank Sta=513.5,527.9
XS Rating Curve= 0 ,0
Exp/Cntr(USF)=0,0
Exp/Cntr=0.3,0.1

Type RM Length L Ch R = 1 ,2823    ,359.4,362.9,365.6
BEGIN DESCRIPTION:
Structure XS 4
END DESCRIPTION:
XS GIS Cut Line= 3
2185930.25492248 633822.558943622186458.63255525 633888.20586163
2186591.52753561633814.553221911
#Sta/Elev= 30
       0 2027.08       6 2022.72    26.1 2011.64    42.2 2005.49    78.5 1988.38
    86.6  1983.5   102.7 1982.24   118.9 1974.85     143 1958.87   151.1 1951.18
   161.8 1942.55   167.2 1940.81   206.3 1938.75   219.6 1940.27   231.7 1939.63
   292.1 1941.51   340.5  1941.8   348.6 1942.76   376.6 1940.92   466.6 1938.69
   477.6  1938.1   493.7 1938.77   505.8 1943.92   517.9 1942.03   525.9 1943.05
   547.9 1953.41   566.2 1960.48   621.1 1975.18   648.5 1983.76   684.4 1991.77
#Mann= 5 ,-1,0
       0      .1       0     350     .06       0     450      .1       0
   466.6    .045       0   493.7      .1       0
#XS Ineff= 2 , 0
          309.31 1954.97
Permanent Ineff=
       F       F
Bank Sta=466.6,493.7
XS Rating Curve= 0 ,0
Exp/Cntr(USF)=0,0
Exp/Cntr=0.3,0.1

Type RM Length L Ch R = 1 ,2460    ,131,131.4,131.4
BEGIN DESCRIPTION:
Structure XS 3
END DESCRIPTION:
XS GIS Cut Line= 6
2185941.81234938633959.9271357912186287.85452661633969.193078724
2186310.99086364634223.9355408822186360.64689896  634241.5070072
2186374.93780765634451.8578418332186558.96726672634439.103737524
#Sta/Elev= 30
       0  2024.2    17.6 2014.61    30.4 2012.64    54.2 1999.79    62.4 2000.28
   134.4 1975.59   157.4 1964.05   186.4  1946.2   206.4 1937.62   309.5  1939.2
   326.5 1937.66   394.6 1937.58   426.7 1936.04   450.8 1936.99   555.2 1933.37
   602.6 1932.96   611.21930.427   632.7 1928.74   640.11930.457   650.6  1936.5
   655.5 1937.09   747.4 1933.72   791.5 1930.04   855.5 1929.77   885.3 1928.32
   903.5 1929.17   918.8 1931.92   959.8 1932.07  1031.9 1960.41  1050.8 1969.74
#Mann= 9 ,-1,0
       0      .1       0     230     .06       0  356.17      .1       0
  547.21     .06       0   611.2    .045       0   640.1     .06       0
   685.3     .07       0   725.3      .1       0   965.6     .06       0
#XS Ineff= 2 , 0
                          673.22         1955.46
Permanent Ineff=
       F       F
Bank Sta=611.2,640.1
XS Rating Curve= 0 ,0
Exp/Cntr(USF)=0,0
Exp/Cntr=0.3,0.1

Type RM Length L Ch R = 1 ,2329    ,137.5,140.8,142.9
BEGIN DESCRIPTION:
Structure XS 2
END DESCRIPTION:
XS GIS Cut Line= 6
2185947.27285111634067.6755604552186250.76995978634063.431931859
2186284.11408874 634350.83932816 2186323.8583581634367.771786704
2186339.17004599634511.7525790532186555.30376678634487.407527019
#Sta/Elev= 30
       0  2029.6    12.9  2020.3    24.9 2018.95    44.9 2006.83    82.3 1989.91
    96.9 1986.38   124.9 1974.47   164.9 1962.79   176.9 1953.25   192.9 1947.15
   204.9 1939.12   208.9 1938.22   276.9 1934.73   303.5 1936.39   450.2  1934.1
   499.5  1930.8   587.4  1931.5     604 1928.18   625.4 1928.24   657.7 1932.45
   722.1 1927.73   786.1 1926.83   798.2 1928.77   862.6 1926.47     882 1930.61
   906.9 1929.59   914.9 1930.94   943.1 1946.55   979.7  1956.8   998.6 1964.08
#Mann= 10 ,-1,0
       0      .1       0     230     .06       0  408.88      .1       0
  427.45     .06       0  509.66     .07       0     604    .045       0
   625.4     .07       0  633.06     .06       0  811.08      .1       0
  911.08     .06       0
#XS Ineff= 2 , 0
          588.45 1940.48
Permanent Ineff=
       F       F
Bank Sta=604,625.4
XS Rating Curve= 0 ,0
Exp/Cntr(USF)=0,0
Exp/Cntr=0.3,0.1

Type RM Length L Ch R = 1 ,2188    ,189.2,186.5,184.9
BEGIN DESCRIPTION:
Structure XS 1
END DESCRIPTION:
XS GIS Cut Line= 4
 2185965.5096489634414.1839315532186128.82637175634399.773632478
2186468.26897219634644.7487167592186597.96166387  634607.9223969
#Sta/Elev= 30
       0 2008.18    14.5 2004.97    26.8 2000.66    50.9 1989.97    70.9 1978.77
      79 1975.41   107.1 1968.55   151.3 1938.03   164.5 1931.44   177.9 1929.83
   237.1 1929.45   253.3 1927.73   291.4  1929.2   299.2 1927.14   303.1 1925.93
   316.1 1925.43   323.6 1927.22   327.8  1929.5   336.4 1931.34   355.5 1928.97
   399.9  1929.1   410.9 1927.02   528.2  1926.2   557.8 1924.36   594.7 1929.65
   611.6 1935.72   661.5 1949.19   694.7 1962.12     703 1963.09   717.4 1969.75
#Mann= 5 ,-1,0
       0      .1       0   299.2    .045       0   323.6      .1       0
  343.95     .06       0  582.56      .1       0
#XS Ineff= 2 , 0
          237.52 1940.84
Permanent Ineff=
       F       F
Bank Sta=299.2,323.6
XS Rating Curve= 0 ,0
Exp/Cntr(USF)=0,0
Exp/Cntr=0.3,0.1

Type RM Length L Ch R = 1 ,2002    ,273.9,267.5,257.9
XS GIS Cut Line= 4
2185930.25492248634605.5185267132186085.56592363634611.923104079
2186407.39593631634768.8352495662186620.34813376634699.986042873
#Sta/Elev= 30
       0 2018.81    29.9 2003.59      42 1998.87      66 1985.34    74.6 1983.11
    97.6 1969.85   116.9 1961.72   128.4 1953.73     150 1932.62   158.3 1927.94
   180.6 1926.17   233.1  1926.4     2461924.561   251.8 1923.75   269.6 1924.64
   298.9 1927.28   319.9 1925.73   340.9 1925.91   354.2 1927.36   443.2 1926.97
   478.8 1923.81   514.3 1923.91   526.9 1922.55   596.4 1924.45   606.8 1926.62
   636.2  1925.5     653 1933.01   686.7 1942.03   729.9 1957.02   737.3 1958.38
#Mann= 8 ,-1,0
       0      .1       0     246    .045       0   269.6     .06       0
  365.44      .1       0  475.44     .06       0  495.44      .1       0
  553.49     .06       0  683.49      .1       0
#XS Ineff= 2 , 0
                          626.59         1940.84
Permanent Ineff=
       F       F
Bank Sta=246,269.6
XS Rating Curve= 0 ,0
Exp/Cntr(USF)=0,0
Exp/Cntr=0.3,0.1

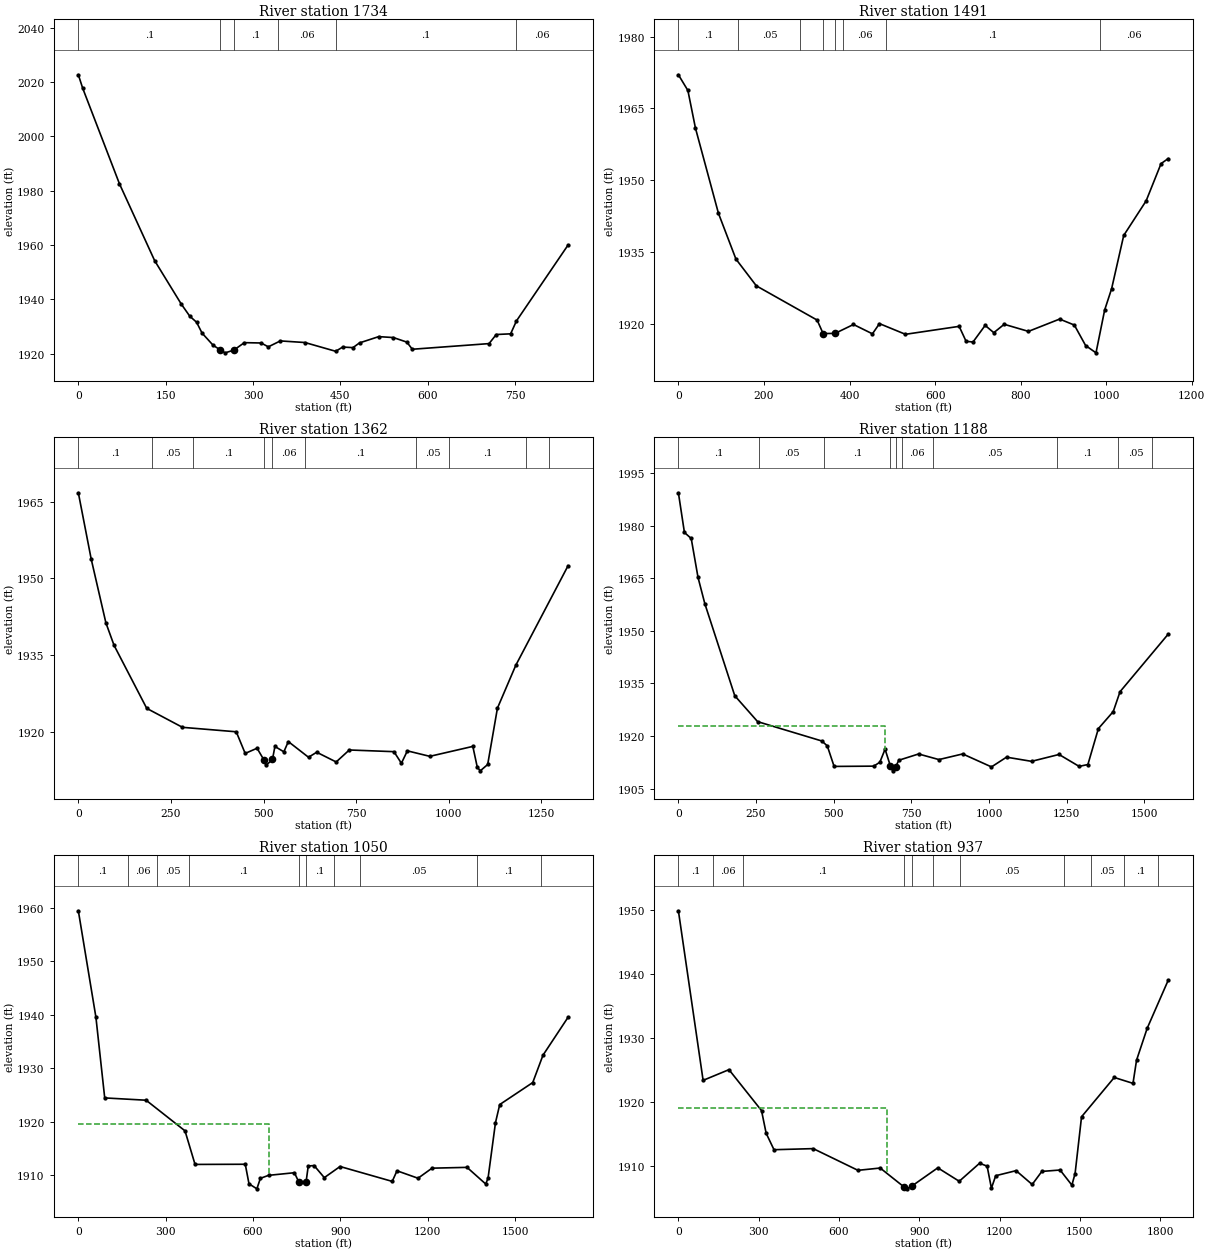
Type RM Length L Ch R = 1 ,1734    ,244,243.1,243.9
XS GIS Cut Line= 3
2185870.06231342634789.1775004862186045.77088316634908.756943777
2186655.87008362634757.452342061
#Sta/Elev= 30
       0 2022.66     7.4 2017.76    70.6 1982.52   131.1 1954.19   176.7 1938.24
   191.3 1933.77   203.1 1931.52   212.5 1927.52   231.5 1923.04   243.9 1921.31
   252.1 1920.25     267 1921.24   285.1    1924   313.9 1923.88   326.3 1922.46
   346.9 1924.64   389.2 1924.05     442 1920.82     454 1922.38   471.7 1922.17
   482.9 1923.91   515.9 1926.22   541.1 1925.88   564.2  1924.2   573.6 1921.57
   705.4 1923.65   717.8    1927   742.5 1927.25   752.4 1931.98   841.1 1959.95
#Mann= 6 ,-1,0
       0      .1       0   243.9    .045       0     267      .1       0
  342.54     .06       0  442.54      .1       0  752.54     .06       0
Bank Sta=243.9,267
XS Rating Curve= 0 ,0
Exp/Cntr(USF)=0,0
Exp/Cntr=0.3,0.1

Type RM Length L Ch R = 1 ,1491    ,129.2,128.9,130.1
XS GIS Cut Line= 3
2185789.52921896634947.8032926072185948.15501108 635147.91583036
2186826.69785975635008.813212654
#Sta/Elev= 30
       0 1972.03    22.2 1968.75    39.9 1960.88    93.6 1943.11   134.5 1933.55
   182.2 1927.96   324.3 1920.81   338.31917.995   366.2 1918.03   409.3 1919.89
   453.6 1917.94     470 1920.07   530.8 1917.84   656.3  1919.5   672.5 1916.38
   688.7 1916.23   717.1  1919.7   737.3 1918.18   761.6 1919.93   818.3 1918.45
   891.2 1921.02   925.6 1919.77   951.9  1915.5   976.2 1913.97   996.5 1922.93
  1012.7 1927.35    1041 1938.48  1093.4  1945.7  1128.3 1953.48  1144.8 1954.52
#Mann= 8 ,-1,0
       0      .1       0     140     .05       0  285.36      .1       0
   338.3    .045       0   366.2      .1       0  385.36     .06       0
  485.36      .1       0  985.36     .06       0
Bank Sta=338.3,366.2
XS Rating Curve= 0 ,0
Exp/Cntr(USF)=0,0
Exp/Cntr=0.3,0.1

Type RM Length L Ch R = 1 ,1362    ,171,173.9,171.6
XS GIS Cut Line= 4
2185758.01694394634973.7038696942185898.14534733635274.596605087
2186692.39067198635199.9163678112186872.50249847635131.481174435
#Sta/Elev= 30
       0 1966.72    34.7 1953.79    74.4 1941.34    96.5 1936.94   184.7 1924.65
   281.2 1920.95   426.4 1920.08   450.5 1915.86   482.6 1916.87   500.61914.648
   506.7 1913.52   524.21914.689   530.8 1917.22   554.9 1916.17     567 1918.17
   621.5 1915.11   643.6 1916.09   696.2 1914.19   731.6 1916.53   852.2  1916.2
   872.3 1913.94   888.4 1916.36     949 1915.29  1065.2 1917.23  1077.2 1913.16
  1085.3 1912.46  1105.3  1913.7  1131.6 1924.69  1181.2 1933.06  1322.3 1952.48
#Mann= 10 ,-1,0
       0      .1       0     200     .05       0     310      .1       0
   500.6    .045       0   524.2     .06       0  611.92      .1       0
  911.92     .05       0 1001.92      .1       0 1209.67     .05       0
 1269.67     .06       0
Bank Sta=500.6,524.2
XS Rating Curve= 0 ,0
Exp/Cntr(USF)=0,0
Exp/Cntr=0.3,0.1

Type RM Length L Ch R = 1 ,1188    ,137.6,138.5,139.1
XS GIS Cut Line= 4
2185684.91438114634919.4345144352185908.85564492635420.868277742
2186690.03563885635323.6244000942186909.67135102 635226.00852802
#Sta/Elev= 30
       0 1989.38    19.4 1978.06    41.3 1976.34    63.2 1965.23    85.1 1957.75
   181.5 1931.49   255.1  1924.1   461.9 1918.58   479.4 1917.18   501.3 1911.33
   629.1 1911.41   648.6 1912.53   665.4 1916.24   682.81911.394   689.6 1910.07
   699.41911.174   709.6 1913.09   773.3 1914.88   838.7 1913.28   915.3 1914.89
    1008 1911.19  1056.4 1913.97    1137 1912.78  1225.5 1914.74  1290.2 1911.34
  1318.4 1911.87  1352.2 1922.12    1400 1926.97  1421.9 1932.64  1576.7 1949.03
#Mann= 10 ,-1,0
       0      .1       0     260     .05       0     470      .1       0
   682.8    .045       0   699.4      .1       0  719.17     .06       0
  819.17     .05       0 1219.17      .1       0 1416.38     .05       0
 1526.38     .06       0
#XS Ineff= 2 , 0
          664.48 1922.96
Permanent Ineff=
       F       F
Bank Sta=682.8,699.4
XS Rating Curve= 0 ,0
Exp/Cntr(USF)=0,0
Exp/Cntr=0.3,0.1

Type RM Length L Ch R = 1 ,1050    ,112.9,113.3,113.5
XS GIS Cut Line= 4
2185678.55572002634997.1152294132185901.23785788 635552.40455553
2186780.33032052635487.1309858192186940.16506081 635362.90283066
#Sta/Elev= 30
       0  1959.4    60.4 1939.51    90.6 1924.45   232.8 1924.02   366.4  1918.3
   400.9 1912.03   573.4 1912.06   586.2 1908.41   613.3 1907.47   625.3 1909.43
   653.4 1909.99   742.2 1910.48   757.91908.676   782.11908.685   789.7 1911.73
   809.8 1911.82   844.9 1909.56     899 1911.64  1078.2 1908.86  1094.6 1910.84
  1166.8 1909.45  1214.9 1911.33  1335.2 1911.48  1399.4 1908.37  1407.4 1909.47
  1432.9 1919.83  1447.5 1923.21  1560.9 1927.32  1596.1 1932.43  1682.2 1939.51
#Mann= 10 ,-1,0
       0      .1       0     170     .06       0     270     .05       0
     380      .1       0   757.9    .045       0   782.1      .1       0
  878.28     .06       0  968.28     .05       0 1368.28      .1       0
 1589.79     .05       0
#XS Ineff= 2 , 0
          655.74 1919.63
Permanent Ineff=
       F       F
Bank Sta=757.9,782.1
XS Rating Curve= 0 ,0
Exp/Cntr(USF)=0,0
Exp/Cntr=0.3,0.1

Type RM Length L Ch R = 1 ,937     ,249.4,245.5,238.8
XS GIS Cut Line= 4
2185644.29853578 635035.159968852185909.33076002635663.058693029
2186799.20830423635607.5442161882186989.73437765635436.228360697
#Sta/Elev= 30
       0 1949.83    92.3 1923.35   188.9 1925.02   310.5 1918.63   327.8 1915.09
   357.1 1912.52   503.7 1912.69   670.8  1909.3   753.9 1909.66   840.91906.769
   852.7 1906.41   872.91906.867     969 1909.69  1049.1 1907.59  1125.2 1910.41
  1153.3 1909.95  1169.3 1906.51  1185.4 1908.46  1261.5 1909.25  1321.6 1907.09
  1357.7 1909.13  1425.8 1909.35  1469.9 1906.99  1481.9  1908.8    1506 1917.66
  1628.2  1923.8  1698.2 1922.88  1711.5  1926.5  1751.1 1931.47  1829.4 1938.95
#Mann= 11 ,-1,0
       0      .1       0     130     .06       0     240      .1       0
   840.9    .045       0   872.9      .1       0  951.54     .06       0
 1051.54     .05       0 1441.54      .1       0 1541.54     .05       0
 1663.15      .1       0 1793.15     .05       0
#XS Ineff= 2 , 0
           779.6    1919
Permanent Ineff=
       F       F
Bank Sta=840.9,872.9
XS Rating Curve= 0 ,0
Exp/Cntr(USF)=0,0
Exp/Cntr=0.3,0.1

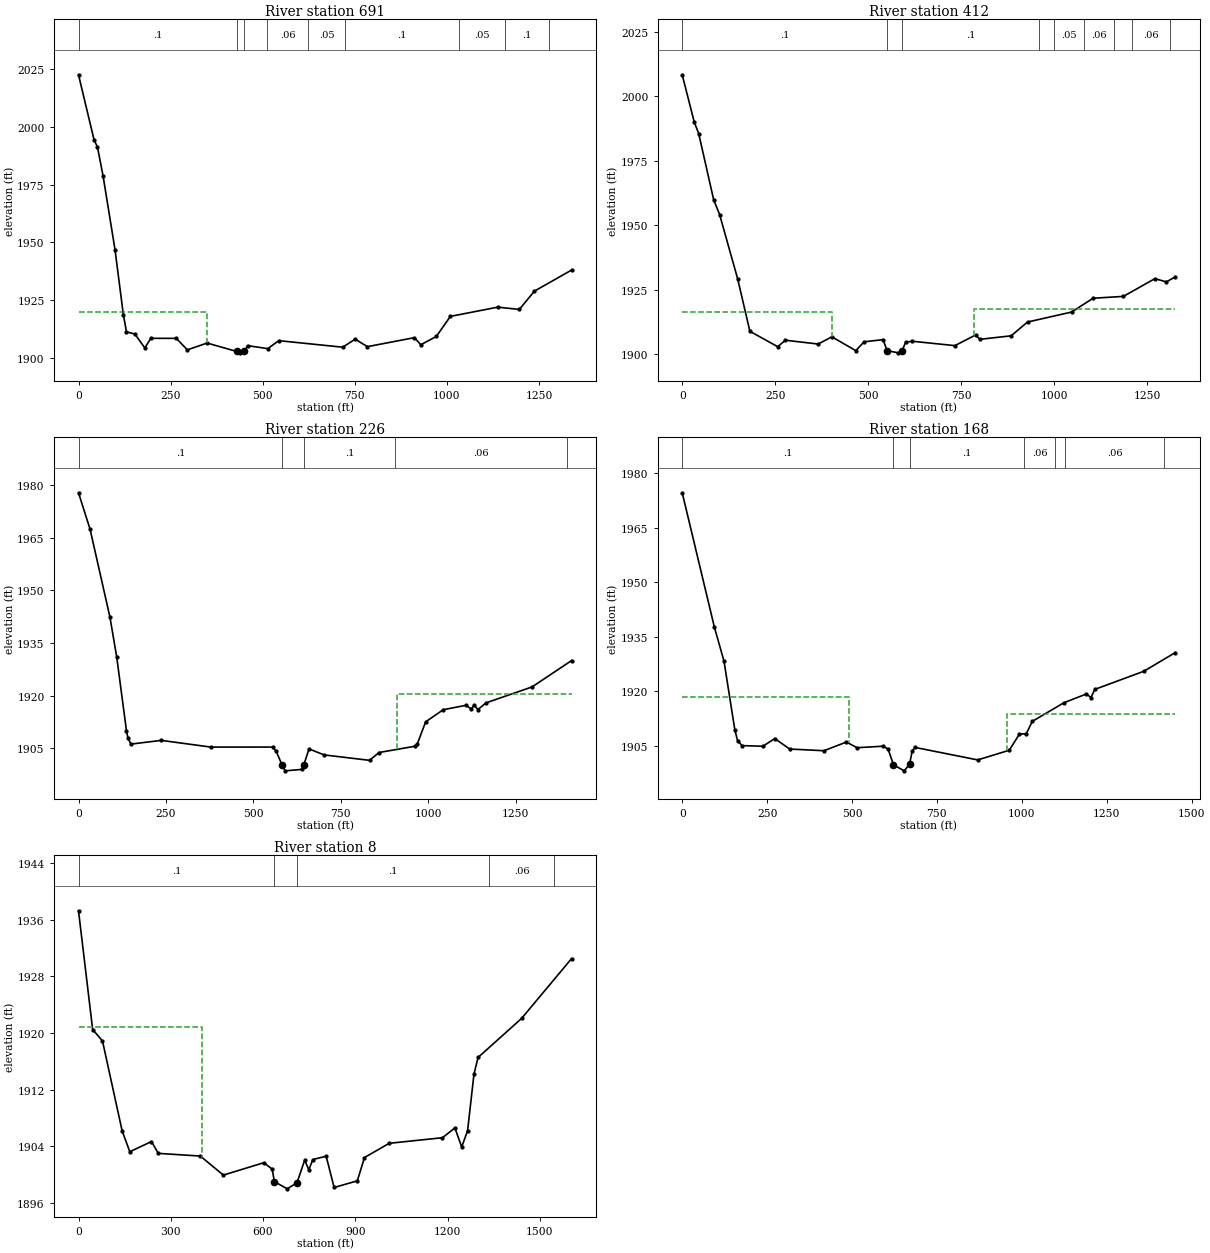
Type RM Length L Ch R = 1 ,691     ,271.3,279.3,280.3
XS GIS Cut Line= 4
2185858.76045175 636103.722463592186120.27996982635866.473449015
2186794.02943945635631.5071645242187007.27247918635462.714404591
#Sta/Elev= 30
       0 2022.68    42.4 1994.34    51.4 1991.43    66.7 1978.81    99.1 1946.88
   121.7 1918.73   130.2 1911.23   153.1 1910.26   180.1 1904.25   196.3 1908.41
   265.7  1908.4   295.5  1903.4   349.1 1906.36   429.2 1902.74   437.7 1902.12
   450.4 1902.71   458.9 1905.25     514 1903.94   543.6  1907.4   717.3 1904.57
   751.2 1908.05   784.3  1904.8   912.2 1908.71   929.1 1905.62   971.5 1909.22
  1009.6 1917.92  1138.2 1921.93  1196.9 1920.94  1237.7 1928.87  1338.6    1938
#Mann= 9 ,-1,0
       0      .1       0   429.2    .045       0   450.4      .1       0
   513.1     .06       0   623.1     .05       0   723.1      .1       0
  1033.1     .05       0 1156.65      .1       0 1276.65     .05       0
#XS Ineff= 2 , 0
          347.73 1919.79
Permanent Ineff=
       F       F
Bank Sta=429.2,450.4
XS Rating Curve= 0 ,0
Exp/Cntr(USF)=0,0
Exp/Cntr=0.3,0.1

Type RM Length L Ch R = 1 ,412     ,193.3,186,180.9
BEGIN DESCRIPTION:
County boundary Structure XS 4
END DESCRIPTION:
XS GIS Cut Line= 4
 2185915.9905326636173.8180058082186088.58811292636159.341319262
2186713.08896306635808.0595910572187050.65316724635533.049996173
#Sta/Elev= 30
       0 2008.31    32.3 1989.97    44.3 1985.53    84.5 1959.89   100.5 1954.15
   148.9  1929.3   181.9  1908.9   256.7 1902.94   277.3 1905.45   365.5 1903.97
   402.2 1906.76   466.5 1901.41   488.8 1904.84   539.9 1905.68   550.5  1901.4
   581.2 1900.56   590.91901.373   600.4 1904.65     618 1905.06   732.9 1903.35
   788.4 1907.48   800.1  1905.8   884.1 1907.16   928.1  1912.5  1046.3 1916.36
  1104.4 1921.72  1185.6 1922.43  1270.3  1929.3  1301.3 1928.06  1325.1    1930
#Mann= 9 ,-1,0
       0      .1       0   550.5    .045       0   590.9      .1       0
  959.72     .06       0  999.72     .05       0 1079.72     .06       0
 1159.72      .1       0 1209.72     .06       0 1309.72     .05       0
#XS Ineff= 2 , 0
          402.91 1916.46  785.43         1917.41
Permanent Ineff=
       F       F
Bank Sta=550.5,590.9
XS Rating Curve= 0 ,0
Exp/Cntr(USF)=0,0
Exp/Cntr=0.3,0.1

Type RM Length L Ch R = 1 ,226     ,55.3,58.1,59.8
BEGIN DESCRIPTION:
Structure XS 3
END DESCRIPTION:
XS GIS Cut Line= 6
2185967.08112923636337.5750328322186110.00949998636342.040911302
2186344.80558953636241.5433903842186452.36102907636187.765670613
2186745.57764401 635934.242134552187049.55174168635532.381842626
#Sta/Elev= 30
       0 1977.75    33.1 1967.36    89.9 1942.34   109.3 1930.98   137.2 1909.97
   141.2 1908.06   149.7 1906.19   236.7 1907.25     379 1905.34   555.1 1905.35
   565.6 1904.09   582.71900.163   591.3 1898.58   638.9 1898.99   644.2 1900.23
   659.4 1904.83     702 1903.12   832.4 1901.57   859.7  1903.8   962.8 1905.59
   968.9 1906.21   992.9 1912.53  1043.2 1915.98  1108.2 1917.24  1123.1  1916.2
  1131.6 1917.22  1142.7 1916.04  1165.9 1917.95  1297.3 1922.47  1410.2 1929.97
#Mann= 5 ,-1,0
       0      .1       0   582.7    .045       0   644.2      .1       0
   906.3     .06       0  1396.3     .05       0
#XS Ineff= 2 , 0
                           912.2         1920.37
Permanent Ineff=
       F       F
Bank Sta=582.7,644.2
XS Rating Curve= 0 ,0
Exp/Cntr(USF)=0,0
Exp/Cntr=0.3,0.1

Type RM Length L Ch R = 1 ,168     ,151.8,159.8,169.5
BEGIN DESCRIPTION:
Structure XS 2
END DESCRIPTION:
XS GIS Cut Line= 6
2185957.15186037636402.4893494872186118.97245328 636400.94031867
2186373.28897765636288.5318004492186480.84441719636234.754080678
2186774.06103213635981.2305446152187078.03512979635579.370252691
#Sta/Elev= 30
       0 1974.64    94.6 1937.67     123 1928.27     155 1909.28   163.1 1906.33
   176.3 1904.99   237.5 1904.81   272.5 1906.94   316.2 1904.05   417.3 1903.58
   483.3 1905.97   514.7 1904.41     592 1904.83   606.2 1904.03   622.1  1899.7
   653.6 1898.04   669.3 1899.83   677.1 1903.44     685  1904.5     870 1901.05
   962.9 1903.71     993 1908.18    1013 1908.26  1030.8 1911.67  1123.7 1916.79
    1190 1919.22  1203.6 1918.23  1214.9 1920.48  1359.1 1925.47  1451.7 1930.61
#Mann= 7 ,-1,0
       0      .1       0   622.1    .045       0   669.3      .1       0
 1007.78     .06       0 1097.78     .05       0 1127.78     .06       0
 1417.78     .05       0
#XS Ineff= 2 , 0
          489.82 1918.28  955.92         1913.77
Permanent Ineff=
       F       F
Bank Sta=622.1,669.3
XS Rating Curve= 0 ,0
Exp/Cntr(USF)=0,0
Exp/Cntr=0.3,0.1

Type RM Length L Ch R = 1 ,8       ,,,
BEGIN DESCRIPTION:
Structure XS 1
END DESCRIPTION:
XS GIS Cut Line= 6
2186010.13659184636527.7020867022186168.90890735636527.702086702
2186729.14354595636268.071517794 2186890.2997139636171.584310281
2186994.10576604 635931.309741542187155.44217835635590.353446343
#Sta/Elev= 30
       0 1937.27      46  1920.5      78 1918.88     142 1906.16   166.8 1903.24
   237.3 1904.68   259.4 1903.01     396 1902.63     471 1899.94   602.4 1901.69
   629.7 1900.79   636.91899.022   678.5    1898   710.4 1898.86   735.4 1902.06
   748.7 1900.69     762 1902.14   805.2 1902.61   831.1 1898.19   906.5 1899.13
   929.8 1902.42  1010.3 1904.43  1183.4 1905.22  1223.8  1906.6  1245.9 1903.91
    1265 1906.21  1285.7 1914.17    1299 1916.55  1440.6 1922.07    1603 1930.51
#Mann= 5 ,-1,0
       0      .1       0   636.9    .045       0   710.4      .1       0
 1335.82     .06       0 1545.82     .05       0
#XS Ineff= 2 , 0
          402.02 1920.79
Permanent Ineff=
       F       F
Bank Sta=636.9,710.4
XS Rating Curve= 0 ,0
Exp/Cntr(USF)=0,0
Exp/Cntr=0.3,0.1
LCMann Table=0

Chan Stop Cuts=-1
Use User Specified Reach Order=0
Composite Channel Slope=5